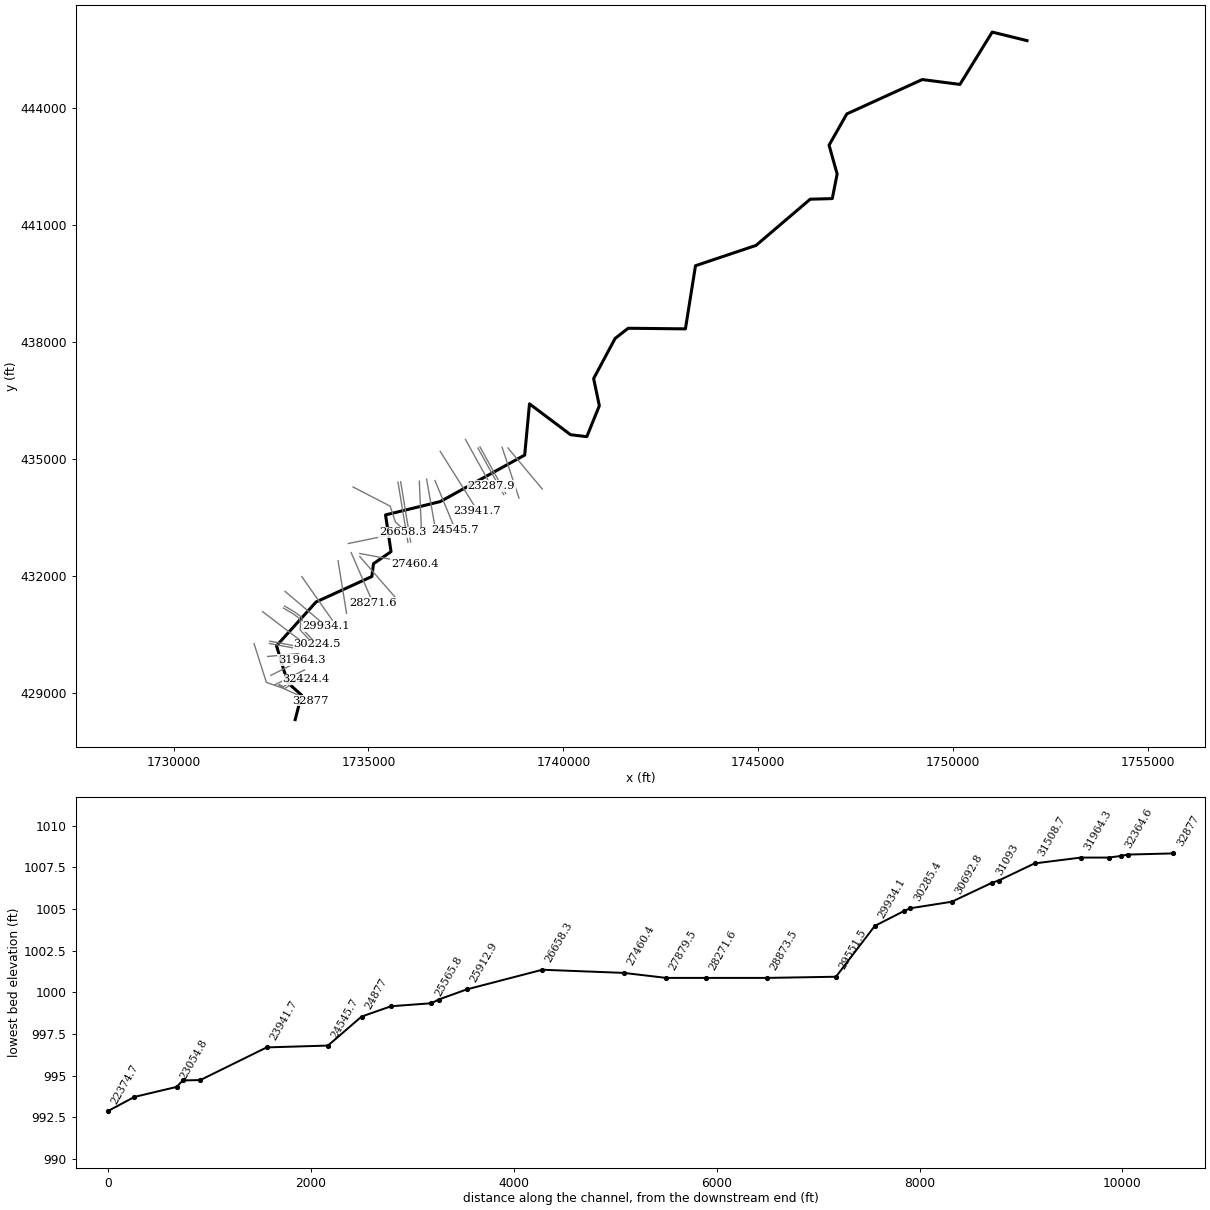
--- WestVaFork.prj (project) ---

Proj Title=WestVaFork
Current Plan=p01
Default Exp/Contr=0,0
English Units
Geom File=g01
Flow File=f01
Plan File=p01
BEGIN DESCRIPTION:
END DESCRIPTION:
DSS Export Rating Curves= 0
DSS Export Rating Curve Sorted= 0
DSS Export Volume Flow Curves= 0
DXF OffsetX= 0
DXF OffsetY= 0
DXF ScaleX= 0
DXF ScaleY= 0

--- WestVaFork.p01 (plan) ---

Plan Title=Floodplain
Program Version=4.00
Geom File=g01
Flow File=f01
K Sum by GR=0
Std Step Tol=0.01
Critical Tol=0.01
Num of Std Step Trials=20
Max Error Tol=0.3
Flow Tol Ratio=0.001
Split Flow NTrial=30
Split Flow Tol=0.02
Split Flow Ratio=0.02
Log Output Level=0
Friction Slope Method=1
Unsteady Friction Slope Method=2
Unsteady Bridges Friction Slope Method=1
Global Log Level=0
CheckData=False
Run HTab=0
Run UNet=0
Run PostProcess=0
UNET Theta=0
UNET Theta Warmup=0
UNET ZTol=0
UNET ZSATol=0
UNET MxIter=0
UNET MaxInSteps=0
UNET DtIC=0
UNET DtMin=0
UNET MaxCRTS=0
UNET WFStab=0
UNET SFStab=0
UNET WFX=0
UNET SFX=0
UNET DSS MLevel=0
UNET DZMax Abort=0
UNET Convert EG Bridges=0
UNET Use Existing IB Tables=0
UNET Froude Limit=0
UNET Froude Power=0
Write IC File=0
Echo Input=False
Echo Output=False
Write Detailed=0

--- WestVaFork.f01 (steady flow) ---

Flow Title=NFF Regression Equation
Program Version=4.10
Number of Profiles= 1
Profile Names=P100yr
River Rch & RM=WestVaFork,Main            ,32877
    4134
River Rch & RM=WestVaFork,Main            ,31154.8
    4140
River Rch & RM=WestVaFork,Main            ,30285.4
    4151
River Rch & RM=WestVaFork,Main            ,27879.5
    4202
River Rch & RM=WestVaFork,Main            ,23287.9
    4556
River Rch & RM=WestVaFork,Main            ,21614.3
    4578
River Rch & RM=WestVaFork,Main            ,13488.6
    4743
River Rch & RM=WestVaFork,Main            ,9269
    4967
River Rch & RM=WestVaFork,Main            ,7978.9
    4974
River Rch & RM=WestVaFork,Main            ,3864.3
    5073
River Rch & RM=WestVaFork,Main            ,495
    5116
River Rch & RM=WestVaFork,Main            ,205.5
    5119
Boundary for River Rch & Prof#=WestVaFork,Main            , 1
Up Type= 0
Dn Type= 3
Dn Slope=0.001
DSS Import GetInterval= 0
DSS Import GetPeak= 0
DSS Import FillOption= 0

--- WestVaFork.g01 (geometry) ---

Geom Title=USGS 10m DEM
Program Version=4.10

River Reach=WestVaFork      ,Main
Reach XY= 30
     1733121.256      428308.324     1733284.227      428939.057
     1732927.175      429258.264     1732642.453      430202.708
     1733658.077      431327.708     1735088.633      431980.486
       1735130.3      432308.611     1735579.953      432617.639
     1735439.328      433560.347     1736843.841      433902.361
     1739008.772      435095.069     1739132.388      436409.279
     1740185.855      435617.639      1740602.79      435567.608
     1740924.026       436360.78     1740777.519       437057.56
     1741328.216      438086.389     1741663.286      438348.542
     1743132.036      438332.917     1743390.716      439952.708
       1744942.8      440473.542     1746333.425      441659.306
     1746899.397      441674.931     1747024.397      442305.139
     1746817.141      443045.281     1747272.661      443846.806
     1749208.425       444728.75     1750174.255      444603.535
     1751002.743      445946.461     1751895.268      445726.739

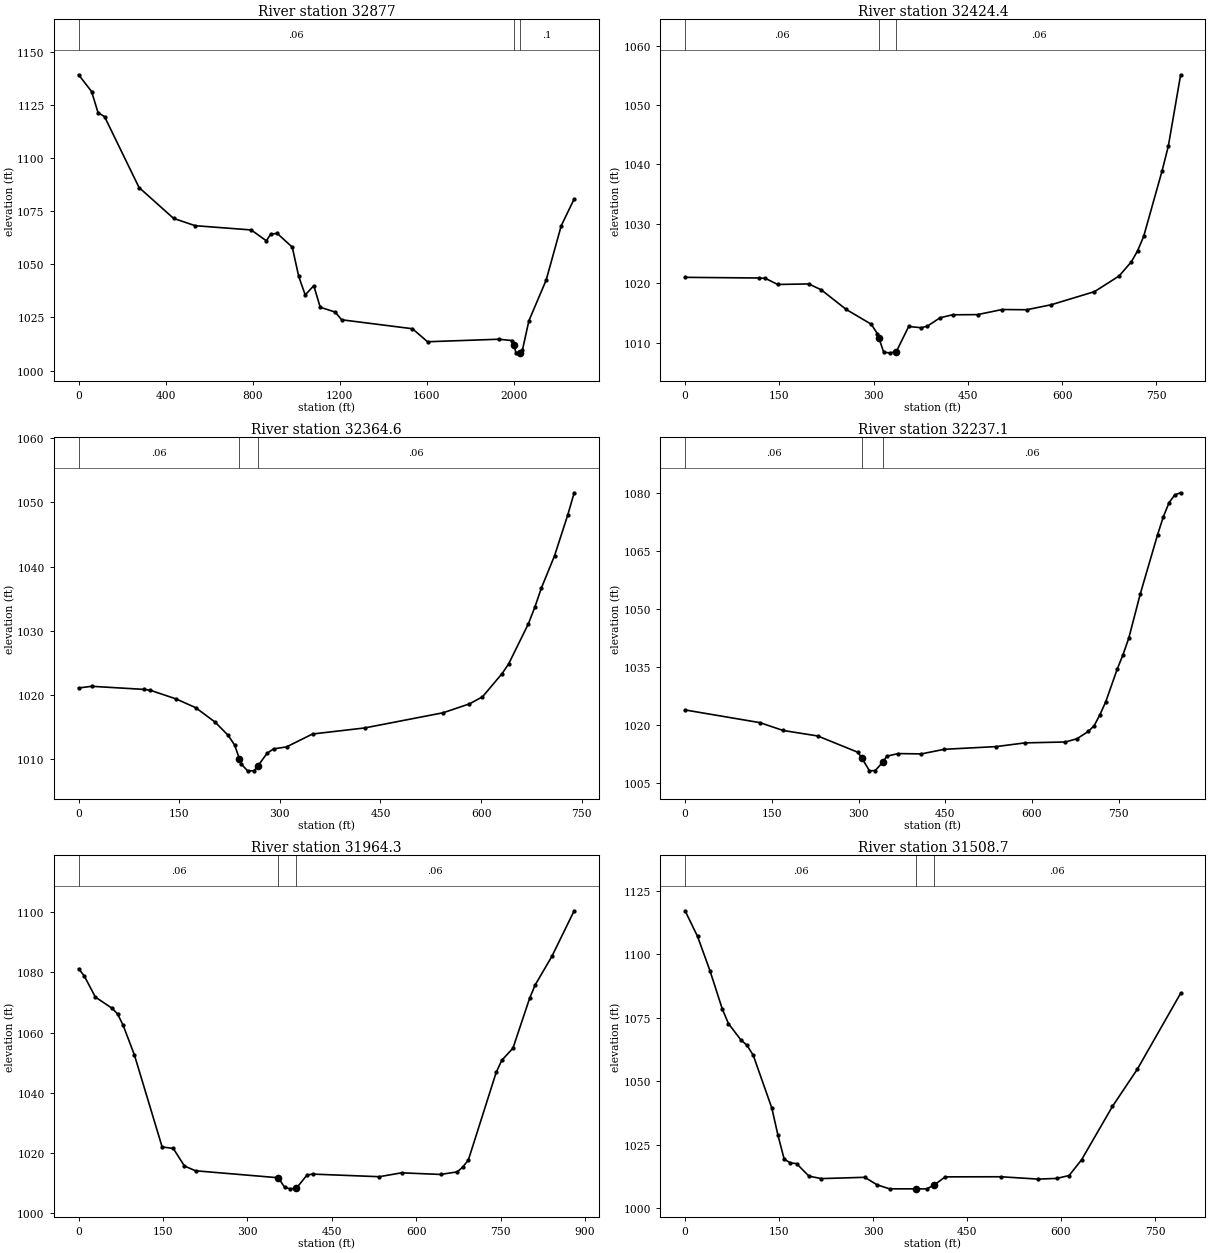
Type RM Length L Ch R = 1 ,32877   ,429.8,452.6,474.5
XS GIS Cut Line= 4
     1732066.556       430257.17     1732382.221      429265.328
     1732808.858      429113.011     1733522.843      428792.766
#Sta/Elev= 30
       0 1139.25    59.5 1131.37    89.2 1121.39     119 1119.55   277.6 1086.16
   436.2 1071.63   535.3  1068.2     793 1066.19   862.4 1061.06   882.2 1064.21
     912 1064.58   981.4  1058.1  1011.1 1044.29  1040.9 1035.59  1080.2 1039.94
  1109.8 1029.81  1178.7 1027.51  1208.3 1023.89  1533.5 1019.68  1602.8 1013.55
  1929.7 1014.74  1989.1 1014.13  1999.4 1012.21    2009 1008.33  2027.6 1008.33
  2038.7 1009.62  2068.4 1023.43  2147.6 1042.55    2217  1068.2  2276.4 1080.77
#Mann= 3 , 0 , 0
       0     .06       0  1999.4    .045       0  2027.6      .1       0
Bank Sta=1999.4,2027.6
XS Rating Curve= 0 ,0
Exp/Cntr=0.3,0.1

Type RM Length L Ch R = 1 ,32424.4 ,59.8,59.8,59.9
XS GIS Cut Line= 4
     1732697.803      429196.021     1732848.522      429103.644
     1733093.835      429255.502      1733405.11      429342.553
#Sta/Elev= 30
       0 1020.98   117.8 1020.87   127.7 1020.81   147.3 1019.78   196.7 1019.87
   216.6 1018.88   256.4 1015.57   296.2 1013.08   306.1 1011.47   308.4 1010.75
   316.1 1008.33     326 1008.26     336 1008.45   355.8  1012.7   375.8 1012.49
   385.7 1012.77   405.6 1014.16   425.5 1014.67   465.3  1014.7   504.5 1015.56
   543.6 1015.52   582.8 1016.37   651.4 1018.57   690.6 1021.21   710.2 1023.61
   719.9 1025.43   729.7 1027.89   759.1 1038.97   768.9 1043.08   788.5 1055.11
#Mann= 3 , 0 , 0
       0     .06       0   308.4    .045       0     336     .06       0
Bank Sta=308.4,336
XS Rating Curve= 0 ,0
Exp/Cntr=0.3,0.1

Type RM Length L Ch R = 1 ,32364.6 ,129.6,127.5,125.4
XS GIS Cut Line= 4
     1732722.112      429205.744     1732814.489      429152.263
     1733069.147        429310.9      1733388.95      429400.336
#Sta/Elev= 30
       0 1021.09    19.4 1021.35      97 1020.87   106.7 1020.74   145.4 1019.38
   174.5 1018.02   203.5 1015.77   222.9 1013.71   232.6  1012.2   239.7 1010.04
   242.2 1009.28   251.9 1008.18   261.6 1008.19   267.5 1008.99     281 1010.92
   290.6  1011.6     310 1011.91   348.7 1013.92   426.3 1014.86   543.5 1017.23
   582.6 1018.61   602.1 1019.71   631.4 1023.34   641.2 1024.86   670.5 1031.08
   680.2 1033.69     690 1036.69   709.5 1041.68   729.1    1048   738.8  1051.5
#Mann= 3 , 0 , 0
       0     .06       0   239.7    .045       0   267.5     .06       0
Bank Sta=239.7,267.5
XS Rating Curve= 0 ,0
Exp/Cntr=0.3,0.1

Type RM Length L Ch R = 1 ,32237.1 ,272.7,272.8,273
XS GIS Cut Line= 2
     1732594.357      429199.537     1733360.386      429583.734
#Sta/Elev= 30
       0 1023.82   129.5 1020.54   169.4 1018.52   229.2  1017.1     299 1012.87
   305.8 1011.36   318.9 1008.08   328.8 1008.16     342 1010.32   348.8 1011.88
   368.7 1012.54   408.6 1012.46   448.4 1013.65   538.1 1014.35   587.9 1015.31
   657.7 1015.54   677.6 1016.37   697.5 1018.28   707.5 1019.77   717.5 1022.62
   727.4 1025.91   747.4  1034.4   757.3  1038.1   767.3 1042.39   787.2 1053.82
   817.1 1069.12   827.1 1073.78     837 1077.43     847 1079.45     857 1079.97
#Mann= 3 , 0 , 0
       0     .06       0   305.8    .045       0     342     .06       0
Bank Sta=305.8,342
XS Rating Curve= 0 ,0
Exp/Cntr=0.3,0.1

Type RM Length L Ch R = 1 ,31964.3 ,464.2,455.6,446.8
XS GIS Cut Line= 2
     1732498.098      429445.069     1733285.292      429839.881
#Sta/Elev= 30
       0 1081.18     9.9 1078.84    29.7 1071.79    59.4 1068.07    69.3 1066.16
    79.2 1062.35      99 1052.62   148.4 1021.99   168.2  1021.5     188 1015.67
   207.8 1014.08   354.9 1011.76   366.1 1008.56     376 1008.08   387.1 1008.32
   405.7 1012.64   415.6 1012.98   534.3 1012.11   573.9  1013.4   643.2 1012.86
   672.9 1013.72   682.8 1015.35   692.6 1017.68   742.1 1046.81     752 1050.79
   771.8  1054.8   801.5 1071.42   811.4 1075.85   841.1 1085.35   880.6 1100.45
#Mann= 3 , 0 , 0
       0     .06       0   354.9    .045       0   387.1     .06       0
Bank Sta=354.9,387.1
XS Rating Curve= 0 ,0
Exp/Cntr=0.3,0.1

Type RM Length L Ch R = 1 ,31508.7 ,360.3,353.9,347.5
XS GIS Cut Line= 2
     1732417.935      429929.322     1733205.559       430001.84
#Sta/Elev= 30
       0 1117.13    19.8 1107.07    39.6 1093.62    59.3 1078.54    69.2 1072.74
      89 1066.34    98.9 1064.18   108.8 1060.26   138.4 1039.55   148.3 1028.75
   158.2 1019.37   168.1 1017.95     178 1017.64   197.7 1012.72   217.5 1011.76
   286.7 1012.27   306.5 1009.31   326.3 1007.73   369.2 1007.73   385.6 1007.73
   397.2 1009.15   415.2 1012.44   504.2 1012.48   563.6 1011.56   593.2 1011.83
     613 1012.97   632.8 1019.15   682.2 1040.18   721.8 1054.77     791 1084.66
#Mann= 3 , 0 , 0
       0     .06       0   369.2    .045       0   397.2     .06       0
Bank Sta=369.2,397.2
XS Rating Curve= 0 ,0
Exp/Cntr=0.3,0.1

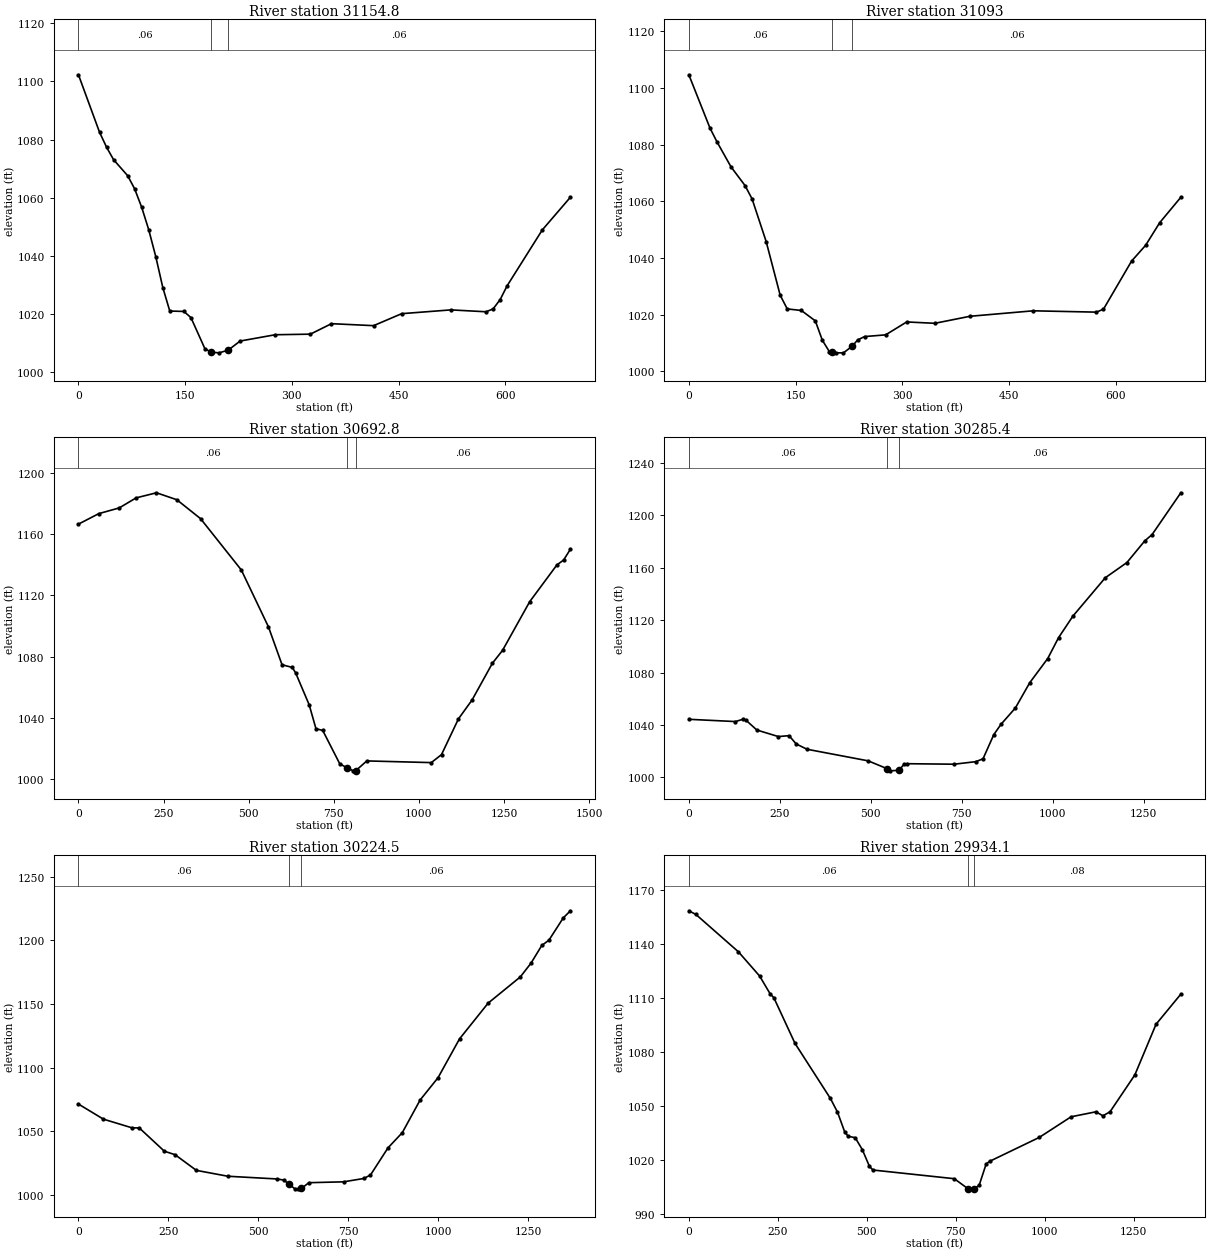
Type RM Length L Ch R = 1 ,31154.8 ,62,61.8,62
XS GIS Cut Line= 2
     1732460.871      430262.033     1733140.728      430135.337
#Sta/Elev= 30
       0 1102.25    29.6 1082.53    39.5 1077.37    49.4 1073.06    69.2 1067.57
      79 1063.05    88.9 1056.71    98.8    1049   108.7 1039.75   118.6 1029.12
   128.4 1021.06   148.2 1020.93   158.1 1018.82   177.8  1008.1   186.6 1006.93
   197.6  1006.7   210.6 1007.62   227.2 1010.75   276.6 1012.92     326 1013.12
   355.7 1016.72   414.9 1016.04   454.4 1020.16   523.6 1021.46     573 1020.81
   582.9  1021.8   592.8 1024.99   602.6 1029.73     652 1048.92   691.6 1060.18
#Mann= 3 , 0 , 0
       0     .06       0   186.6    .045       0   210.6     .06       0
Bank Sta=186.6,210.6
XS Rating Curve= 0 ,0
Exp/Cntr=0.3,0.1

Type RM Length L Ch R = 1 ,31093   ,410.5,400.1,389.1
XS GIS Cut Line= 2
     1732471.863      430321.017      1733151.72      430194.322
#Sta/Elev= 30
       0 1104.69    29.6 1085.96    39.5 1081.04    59.3 1072.19      79  1065.6
    88.9 1060.89   108.7 1045.85   128.4 1026.91   138.3 1022.08   158.1 1021.53
   177.8 1017.86   187.7    1011   197.6 1006.98   200.7 1006.85   207.5 1006.58
   217.4 1006.58     230    1009   237.1 1011.09     247 1012.32   276.6 1012.92
   306.3 1017.48   345.8    1017   395.2 1019.48   484.1 1021.41     573 1020.94
   582.9 1021.99   622.4 1038.96   642.2 1044.55   661.9  1052.5   691.6 1061.46
#Mann= 3 , 0 , 0
       0     .06       0   200.7    .045       0     230     .06       0
Bank Sta=200.7,230
XS Rating Curve= 0 ,0
Exp/Cntr=0.3,0.1

Type RM Length L Ch R = 1 ,30692.8 ,423.6,407.5,391.4
XS GIS Cut Line= 2
     1732285.559      431078.901     1733434.179      430201.978
#Sta/Elev= 30
       0 1166.61    59.8 1173.47   119.6 1177.18   169.4 1183.76   229.2 1187.09
     289 1182.54   358.8 1170.15   478.4 1136.65   558.1 1099.49     598 1074.74
   627.9    1073   637.8  1069.5   677.7 1048.59   697.6 1032.99   717.6 1031.79
   767.4  1010.1   787.4 1007.53   807.3 1005.43   813.9 1005.43   847.1 1011.91
  1036.5 1010.81  1066.4 1016.02  1116.2 1039.39  1156.1 1051.68  1215.9 1075.73
  1245.8 1084.17  1325.5 1115.95  1405.2 1139.91  1425.2 1143.17  1445.1 1150.25
#Mann= 3 , 0 , 0
       0     .06       0   787.4    .045       0   813.9     .06       0
Bank Sta=787.4,813.9
XS Rating Curve= 0 ,0
Exp/Cntr=0.3,0.1

Type RM Length L Ch R = 1 ,30285.4 ,61.1,60.8,60.6
XS GIS Cut Line= 6
     1732819.691      431170.305     1733082.083      431014.941
     1733231.515      430901.242     1733259.619      430766.968
     1733248.575      430608.663     1733636.119      430199.787
#Sta/Elev= 30
       0 1044.36   127.9 1042.64   147.6  1044.3   157.4 1043.56   186.9 1036.18
   245.9  1031.2   275.4 1031.88   295.1 1025.54   324.7 1021.51   492.7 1012.67
   544.4 1006.73   551.5 1005.04   577.6 1005.43   590.7  1009.9   600.5 1010.48
   729.1  1010.1   788.6 1012.05   808.4 1014.24     838 1032.66   857.8 1040.57
   897.3    1053   936.8 1072.29   986.2 1090.75  1015.9 1106.64  1055.4 1123.11
  1144.4 1152.38  1203.7 1163.95  1253.1 1180.59  1272.9 1185.29  1351.9  1217.2
#Mann= 3 , 0 , 0
       0     .06       0   544.4    .045       0   577.6     .06       0
Bank Sta=544.4,577.6
XS Rating Curve= 0 ,0
Exp/Cntr=0.3,0.1

Type RM Length L Ch R = 1 ,30224.5 ,275.2,290.4,305.6
XS GIS Cut Line= 6
      1732850.26      431221.933     1733115.646      431064.797
     1733285.658       430935.44     1733320.054      430771.104
     1733310.265      430630.797     1733679.666      430241.062
#Sta/Elev= 30
       0 1071.43    69.6 1059.56   149.2 1052.75   169.1  1052.7   238.8 1034.42
   268.6 1031.68   327.8 1019.38   415.2 1014.77   551.7 1012.64   571.4 1011.72
   586.5 1008.33   601.1 1005.01   610.9 1004.88   619.8  1005.2   640.6 1009.71
   736.8 1010.38   793.1 1013.01   811.8 1015.74   860.4 1037.02   900.2 1048.98
   949.9 1074.66   999.6 1092.14  1059.3  1122.6  1138.9 1150.69  1228.4 1171.28
  1258.2 1182.13    1288 1195.97  1307.9 1200.11  1347.7 1217.59  1367.6 1223.18
#Mann= 3 , 0 , 0
       0     .06       0   586.5    .045       0   619.8     .06       0
Bank Sta=586.5,619.8
XS Rating Curve= 0 ,0
Exp/Cntr=0.3,0.1

Type RM Length L Ch R = 1 ,29934.1 ,388.4,382.6,376.8
XS GIS Cut Line= 2
     1732863.166      431596.969     1733917.887       430702.64
#Sta/Elev= 30
       0 1158.66    19.9 1156.61   139.3 1135.84     199 1122.35   228.8 1112.36
   238.8 1110.36   298.5 1084.85   397.9 1054.26   417.8 1046.65   437.7 1035.85
   447.7 1033.21   467.6 1032.44   487.5 1025.82   507.4 1016.59   517.3 1014.45
   746.1 1009.62   784.4 1004.07   785.9 1003.98   801.2 1004.03   815.8 1005.84
   835.7 1017.83   845.6  1019.3   984.9 1032.58  1074.4 1044.06  1144.1 1046.83
    1164  1044.6  1183.9 1046.86  1253.5 1067.32  1313.2 1095.54  1382.8 1112.27
#Mann= 3 , 0 , 0
       0     .06       0   784.4    .045       0   801.2     .08       0
Bank Sta=784.4,801.2
XS Rating Curve= 0 ,0
Exp/Cntr=0.3,0.1

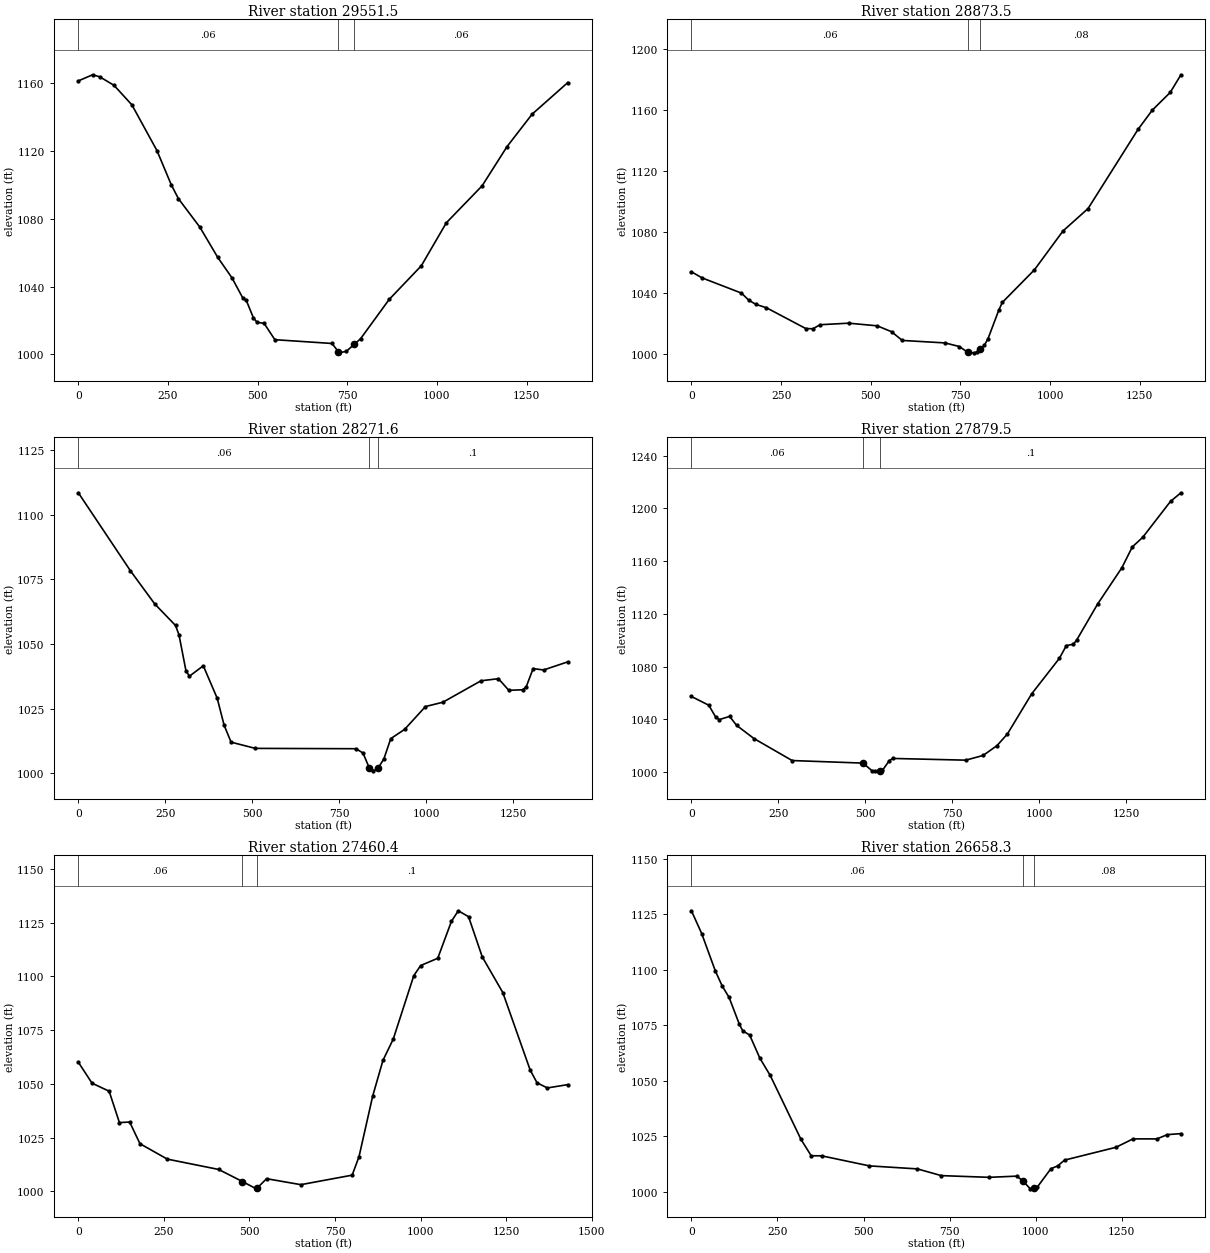
Type RM Length L Ch R = 1 ,29551.5 ,688.2,678,667.8
XS GIS Cut Line= 2
     1733289.491      431978.879     1734073.536      430861.516
#Sta/Elev= 30
       0  1161.2    39.8  1164.8    59.8  1163.6    99.6 1158.56   149.4 1147.06
   219.2 1120.14     259 1100.05     279 1091.82   338.8 1075.03   388.6 1057.23
   428.4 1045.13   458.3 1033.39   468.3 1031.88   488.2 1021.56   498.2 1018.94
   518.1 1018.28     548 1008.68   707.4 1006.45   724.9 1001.65   727.3 1000.93
   747.3 1001.84   769.9 1006.01   787.1 1009.26   866.8  1032.4   956.5 1052.26
  1026.2 1077.58  1125.9 1099.34  1195.6 1122.53  1265.4 1141.58    1365 1160.24
#Mann= 3 , 0 , 0
       0     .06       0   724.9    .045       0   769.9     .06       0
Bank Sta=724.9,769.9
XS Rating Curve= 0 ,0
Exp/Cntr=0.3,0.1

Type RM Length L Ch R = 1 ,28873.5 ,596.3,601.9,607.1
XS GIS Cut Line= 2
     1734220.568      432383.482     1734439.238      431036.111
#Sta/Elev= 30
       0 1053.91    29.9  1049.9   139.5 1039.96   159.4 1035.43   179.3 1032.62
   209.2 1030.37   318.8 1016.77   338.8 1016.61   358.7 1019.26   438.4 1020.28
   518.1 1018.54     558 1014.69   587.8 1008.98   707.4 1007.35   747.3 1004.97
   770.9 1001.13   787.1 1000.86   797.1 1001.32   805.7 1003.22     817 1005.88
     827 1010.09   856.9  1028.7   866.8 1033.84   956.5 1055.22  1036.2 1080.66
    1106 1095.31  1245.4 1147.15  1285.3 1159.78  1335.1  1171.3    1365 1182.88
#Mann= 3 , 0 , 0
       0     .06       0   770.9    .045       0   805.7     .08       0
Bank Sta=770.9,805.7
XS Rating Curve= 0 ,0
Exp/Cntr=0.3,0.1

Type RM Length L Ch R = 1 ,28271.6 ,390.7,392.1,390.3
XS GIS Cut Line= 2
      1734557.89      432592.089     1735117.816      431300.885
#Sta/Elev= 30
       0 1108.58   149.7 1078.38   219.6 1065.53   279.5 1057.17   289.5 1053.49
   309.4 1039.66   319.4 1037.52   359.3 1041.56   399.3 1028.97   419.2 1018.52
   439.2 1011.97     509 1009.56   798.5 1009.43   818.5 1007.76   836.9 1001.85
   848.4 1000.86   861.3 1001.82   878.4 1005.45   898.3 1013.34   938.2 1016.93
   998.1 1025.77    1048 1027.43  1157.8 1035.75  1207.8 1036.56  1237.7 1032.06
  1277.6 1032.26  1287.6 1033.36  1307.6 1040.48  1337.5 1039.93  1407.4 1043.09
#Mann= 3 , 0 , 0
       0     .06       0   836.9    .045       0   861.3      .1       0
Bank Sta=836.9,861.3
XS Rating Curve= 0 ,0
Exp/Cntr=0.3,0.1

Type RM Length L Ch R = 1 ,27879.5 ,397.4,419.2,444.7
XS GIS Cut Line= 2
     1734777.844       432493.74     1735700.677      431431.147
#Sta/Elev= 30
       0 1057.25    49.9 1050.63    69.9 1041.56    79.8 1039.72   109.8 1042.14
   129.8 1035.35   179.7 1025.38   289.5 1008.67   493.1 1006.73     519    1001
     529 1000.86   542.2 1000.97     549 1001.19   568.9 1008.59   578.9 1010.26
   788.5 1008.96   838.4  1012.5   878.4 1019.96   908.3 1028.75   978.2 1059.25
    1058 1086.22    1078 1095.91    1098 1096.87  1107.9 1100.18  1167.8 1127.37
  1237.7 1154.98  1267.6 1170.72  1297.6 1178.02  1377.4 1205.25  1407.4 1211.78
#Mann= 3 , 0 , 0
       0     .06       0   493.1    .045       0   542.2      .1       0
Bank Sta=493.1,542.2
XS Rating Curve= 0 ,0
Exp/Cntr=0.3,0.1

Type RM Length L Ch R = 1 ,27460.4 ,793.8,802.1,809.4
XS GIS Cut Line= 2
     1734780.375      432569.418     1736186.082      432307.494
#Sta/Elev= 30
       0 1060.11      40 1050.34      90  1046.6     120    1032     150 1032.25
     180 1022.17     260 1014.99     410 1010.18   479.3 1004.56     520 1001.16
     521 1001.32     550 1005.88     650  1003.1   799.9 1007.53   819.9 1016.13
   859.9 1044.37   889.9 1060.98   919.9 1070.86   979.9 1100.37   999.9 1105.09
  1049.9 1108.47  1089.9 1125.68  1109.9 1130.58  1139.9 1127.83  1179.9 1109.12
  1239.9 1092.53  1319.9 1056.44  1339.9 1050.53  1369.9 1048.12  1429.9 1049.67
#Mann= 3 , 0 , 0
       0     .06       0   479.3    .045       0     521      .1       0
Bank Sta=479.3,521
XS Rating Curve= 0 ,0
Exp/Cntr=0.3,0.1

Type RM Length L Ch R = 1 ,26658.3 ,778.1,745.4,712.6
XS GIS Cut Line= 2
      1734484.09      432826.614      1735877.32      433113.072
#Sta/Elev= 30
       0 1126.52    29.8 1116.27    69.6 1099.38    89.5 1092.62   109.4 1087.53
   139.2 1075.46   149.2 1072.44   169.1 1070.61   198.9 1060.15   228.8 1052.43
   318.3 1023.62   348.1 1016.23     378 1016.22   517.2 1011.68   656.5 1010.33
   726.1  1007.3   865.4 1006.53   944.9 1007.07   962.3 1005.04   984.7 1001.35
   996.7 1001.52  1004.6 1002.06  1044.4 1010.39  1064.3 1011.68  1084.2 1014.28
  1233.4 1020.04  1283.1 1023.84  1352.8 1023.83  1382.6 1025.75  1422.4 1026.21
#Mann= 3 , 0 , 0
       0     .06       0   962.3    .045       0   996.7     .08       0
Bank Sta=962.3,996.7
XS Rating Curve= 0 ,0
Exp/Cntr=0.3,0.1

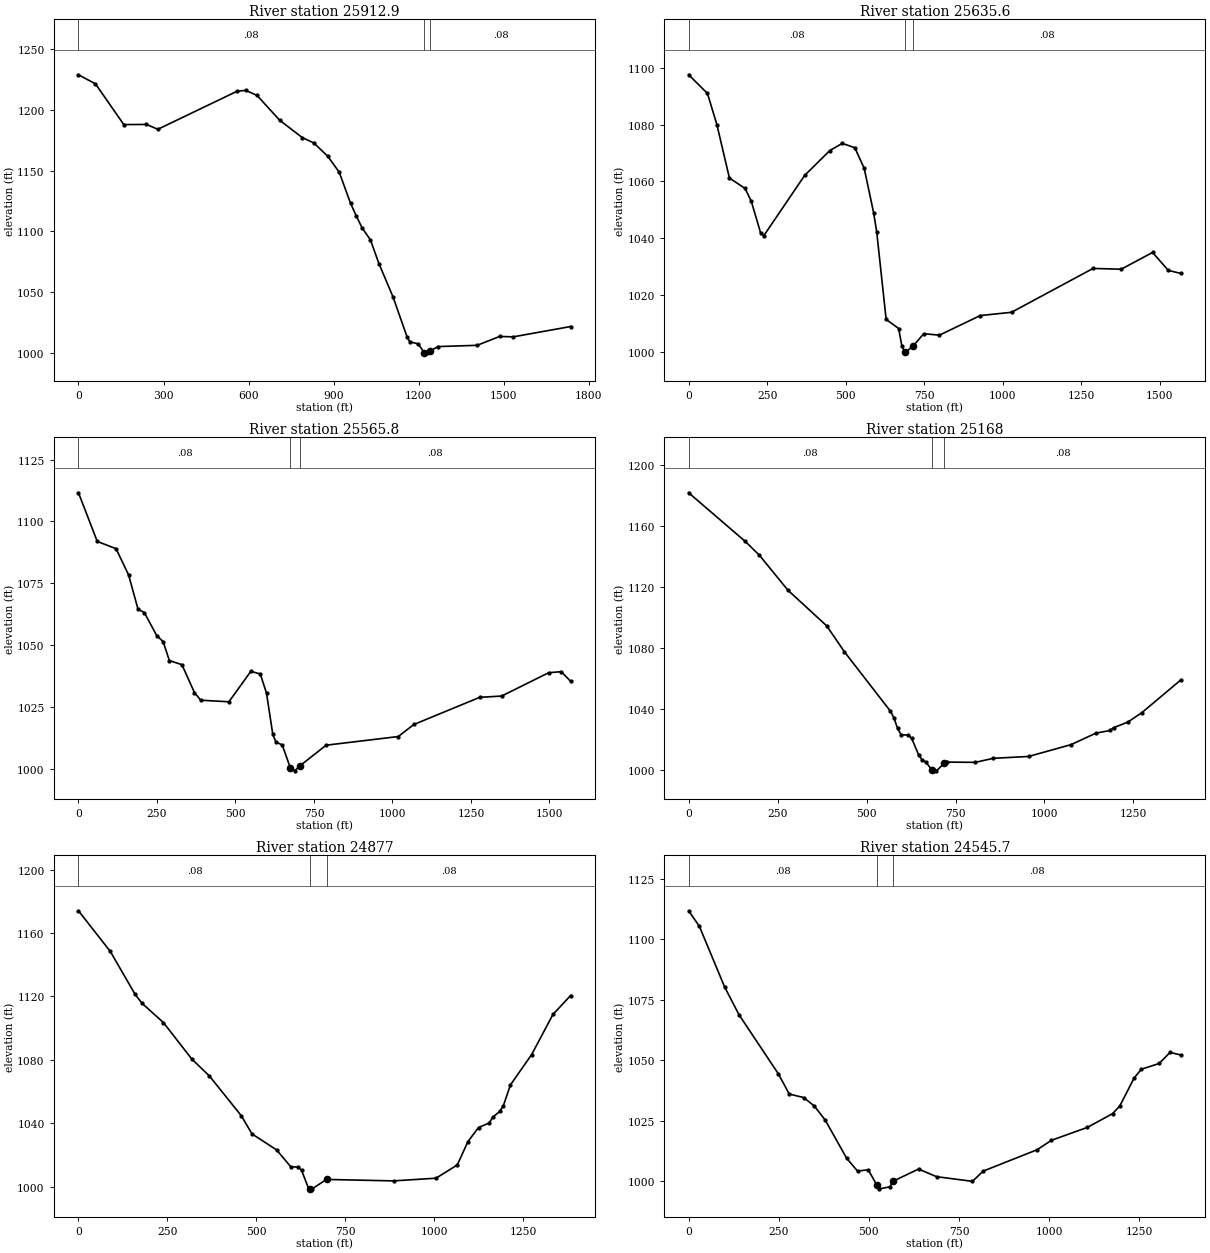
Type RM Length L Ch R = 1 ,25912.9 ,280.9,277.3,273.6
XS GIS Cut Line= 4
     1734605.618      434276.267     1735556.139      433785.815
     1735695.028      433373.489     1735868.639      433221.579
#Sta/Elev= 30
       0 1228.68      60 1221.22   159.9 1187.75   239.9 1187.86   279.9 1183.88
   559.8  1215.2   589.8 1215.85   629.8 1211.71   709.7 1191.27   789.7 1176.98
   829.7 1172.69   879.7 1161.55   919.6 1148.56   959.6 1122.94   979.6 1112.71
   999.6 1103.08  1029.6 1092.96  1059.6 1073.45  1109.2 1046.15  1158.6 1013.32
  1168.5 1009.24  1198.1 1007.54    1219 1000.36  1227.8 1000.17  1240.3  1001.6
  1267.4 1005.32  1405.8 1006.35  1484.9 1013.62  1533.5 1013.33  1735.4 1021.78
#Mann= 3 , 0 , 0
       0     .08       0    1219    .045       0  1240.3     .08       0
Bank Sta=1219,1240.3
XS Rating Curve= 0 ,0
Exp/Cntr=0.3,0.1

Type RM Length L Ch R = 1 ,25635.6 ,69.8,69.8,69.8
XS GIS Cut Line= 2
     1735758.249      434403.033      1736013.46      432856.436
#Sta/Elev= 30
       0  1097.6    59.9 1091.02    89.9 1080.01   129.8 1061.19   179.7 1057.53
   199.7 1052.93   229.6 1041.69   239.6 1040.91   369.4 1062.11   449.3 1070.86
   489.2 1073.41   529.2 1071.88   559.1 1064.62   589.1 1048.96     599 1042.15
     629 1011.33   668.9 1008.14   678.9 1002.04     688  999.78   688.9  999.56
   715.7 1002.08   748.8 1006.31   798.7 1005.79   928.5  1012.7  1028.4 1013.86
    1288 1029.32  1377.8 1029.05  1477.6 1034.96  1527.6 1028.63  1567.5 1027.56
#Mann= 3 , 0 , 0
       0     .08       0     688    .045       0   715.7     .08       0
Bank Sta=688,715.7
XS Rating Curve= 0 ,0
Exp/Cntr=0.3,0.1

Type RM Length L Ch R = 1 ,25565.8 ,400.5,397.9,395.1
XS GIS Cut Line= 2
     1735827.865       434409.33     1736083.076      432862.733
#Sta/Elev= 30
       0 1111.58    59.9 1091.94   119.8    1089   159.8 1078.39   189.7 1064.57
   209.7 1063.25   249.6 1053.87   269.6 1051.53   289.5 1043.85   329.5  1042.2
   369.4 1030.94   389.4 1027.85   479.2 1027.21   549.1 1039.51   579.1 1038.44
     599 1030.66     619 1014.02     629 1010.95     649 1009.79   674.7 1000.57
   688.9  999.34     705 1001.34   788.8 1009.69  1018.4 1013.18  1068.3 1018.05
    1278 1029.01  1347.9 1029.53  1497.6 1038.95  1537.6 1039.37  1567.5 1035.49
#Mann= 3 , 0 , 0
       0     .08       0   674.7    .045       0     705     .08       0
Bank Sta=674.7,705
XS Rating Curve= 0 ,0
Exp/Cntr=0.3,0.1

Type RM Length L Ch R = 1 ,25168   ,287.9,290.9,293.9
XS GIS Cut Line= 2
     1736305.888      434426.034     1736365.463      433044.191
#Sta/Elev= 30
       0  1181.9   159.2  1149.9     199  1140.8   278.6 1117.96   388.1  1094.4
   437.8 1077.37   567.2 1038.31   577.1 1033.87   587.1 1027.04     597  1022.9
   616.9 1022.63   626.9 1020.46   646.8 1009.33   656.7 1006.29   666.7 1004.94
     683  999.88   686.6  999.16   696.5  999.16   717.7 1004.05   726.4  1004.9
     806 1004.75   855.8 1007.39   955.2  1008.6  1074.7 1016.39  1144.3  1023.9
  1184.1 1025.69  1194.1 1027.54  1233.9 1031.15  1273.7 1037.41  1383.1  1058.9
#Mann= 3 , 0 , 0
       0     .08       0     683    .045       0   717.7     .08       0
Bank Sta=683,717.7
XS Rating Curve= 0 ,0
Exp/Cntr=0.3,0.1

Type RM Length L Ch R = 1 ,24877   ,326.4,331.4,336.3
XS GIS Cut Line= 2
     1736492.863      434476.854     1736732.486      433114.643
#Sta/Elev= 30
       0 1173.98    89.6 1148.29   159.2 1121.24   179.1 1115.48   238.8 1103.46
   318.4 1080.47   368.2 1069.69   457.7 1044.65   487.6 1033.22   557.2 1023.04
     597 1012.37   616.9 1012.34   626.9 1010.24   646.8  998.74   651.7  998.64
   656.7  998.54   697.1 1004.47   885.6 1003.56    1005 1005.26  1064.7 1013.63
  1094.6 1028.39  1124.4 1037.24  1154.3 1040.06  1164.2 1043.74  1184.1  1047.4
  1194.1 1050.98    1214 1064.11  1273.7 1083.29  1333.4 1108.54  1383.1 1120.51
#Mann= 3 , 0 , 0
       0     .08       0   651.7    .045       0   697.1     .08       0
Bank Sta=651.7,697.1
XS Rating Curve= 0 ,0
Exp/Cntr=0.3,0.1

Type RM Length L Ch R = 1 ,24545.7 ,600.1,603.9,607.7
XS GIS Cut Line= 2
     1736708.005      434441.656     1737228.983      433179.987
#Sta/Elev= 30
       0  1111.8    29.9  1105.3    99.6 1080.34   139.5 1068.83   249.1 1044.28
     279 1036.01   318.8 1034.56   348.7 1031.04   378.6 1025.26   438.4  1009.4
   468.3 1004.16   498.2 1004.66   521.4  998.49   528.1   996.8     558   997.6
   566.6  999.94   637.7 1004.98   687.5 1001.83   787.1   999.9     817 1004.14
   966.5 1012.97  1006.3 1016.88    1106 1022.22  1175.7  1027.9  1195.6 1031.02
  1235.5 1042.63  1255.4 1046.24  1305.2 1048.66  1335.1 1053.23    1365 1052.16
#Mann= 3 , 0 , 0
       0     .08       0   521.4    .045       0   566.6     .08       0
Bank Sta=521.4,566.6
XS Rating Curve= 0 ,0
Exp/Cntr=0.3,0.1

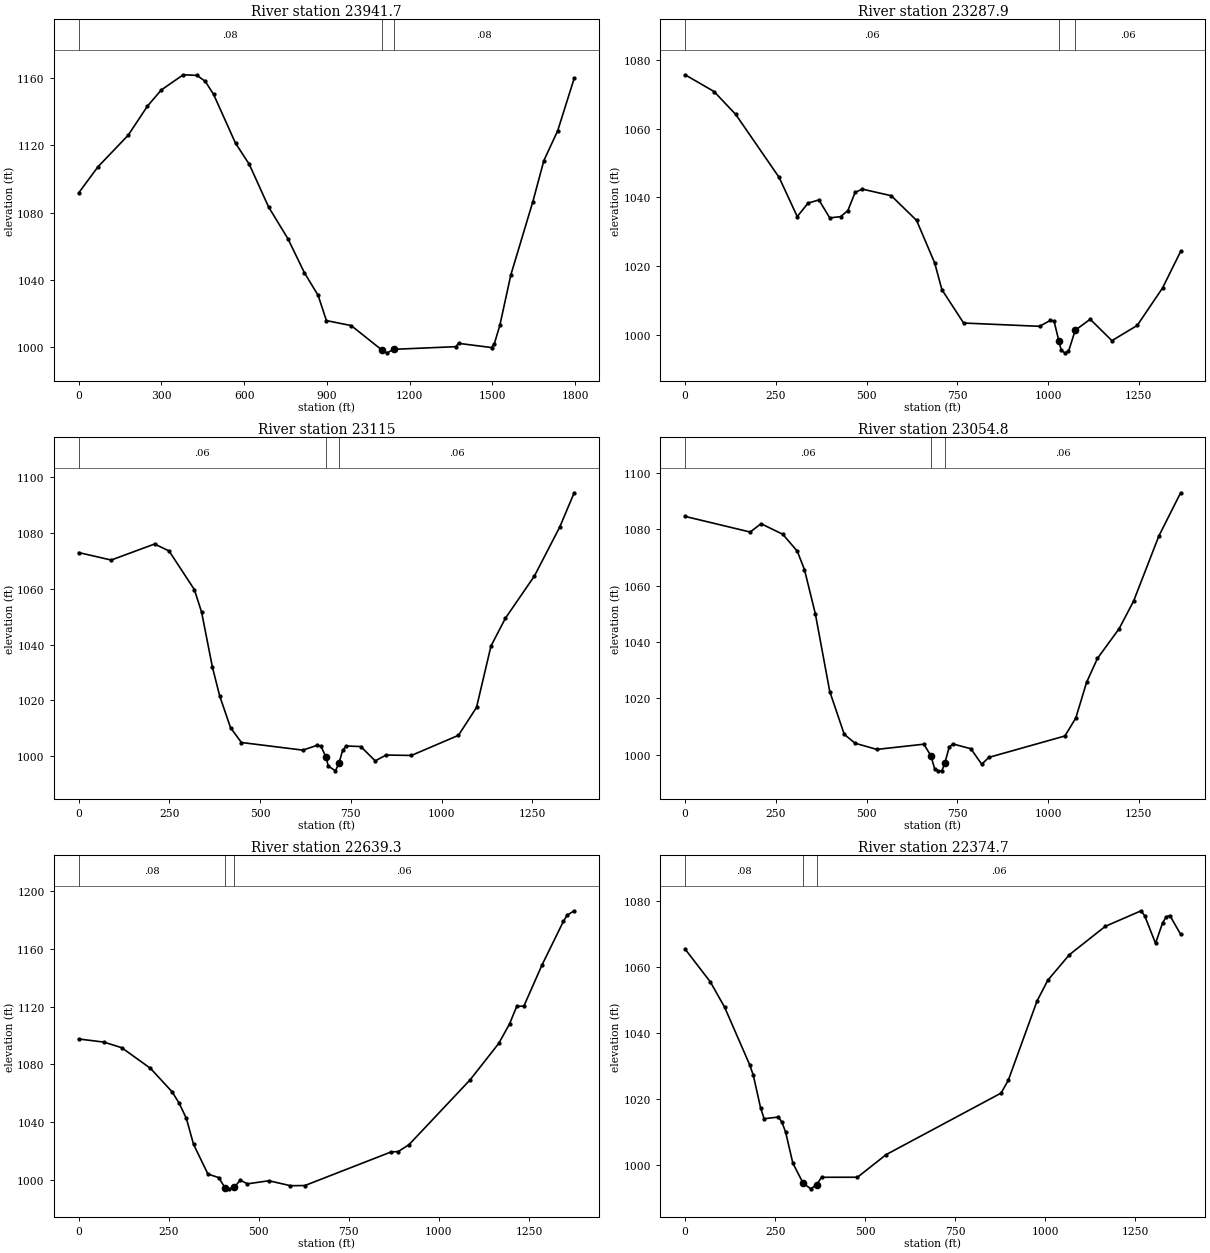
Type RM Length L Ch R = 1 ,23941.7 ,655,653.8,652.6
XS GIS Cut Line= 2
     1736839.993      435192.933      1737796.02      433671.501
#Sta/Elev= 30
       0 1091.65    69.9 1107.15   179.7 1125.97   249.6 1143.25   299.5  1152.8
   379.3 1161.86   429.2  1161.5   459.2 1157.94   489.2 1150.27     569 1121.18
   618.9 1108.65   688.8 1083.33   758.7 1064.55   818.6  1044.3   868.5 1030.81
   898.4 1015.84   988.3 1012.89  1098.7  998.49    1118  996.69  1143.7  998.79
  1367.6 1000.35  1377.6 1002.33  1497.4  999.82  1507.4  1002.1  1527.3 1012.99
  1567.3 1043.01  1647.1 1086.52  1687.1 1110.93    1737 1128.56  1796.9 1159.72
#Mann= 3 , 0 , 0
       0     .08       0  1098.7    .045       0  1143.7     .08       0
Bank Sta=1098.7,1143.7
XS Rating Curve= 0 ,0
Exp/Cntr=0.3,0.1

Type RM Length L Ch R = 1 ,23287.9 ,172.9,172.9,172.9
XS GIS Cut Line= 2
     1737489.653      435495.033     1738151.184      434301.048
#Sta/Elev= 30
       0 1075.68    79.7 1070.81   139.5 1064.13     259  1045.8   308.9  1034.4
   338.8 1038.33   368.6 1039.24   398.5 1034.02   428.4 1034.38   448.4 1036.16
   468.3 1041.44   488.2 1042.39   567.9 1040.47   637.7 1033.28   687.5  1020.9
   707.4 1013.12   767.2 1003.41   976.4 1002.45  1006.3  1004.2  1016.3 1003.97
  1029.6  998.17  1036.2  995.43  1046.2  994.73  1056.1  995.12  1074.6  1001.3
  1115.9 1004.51  1175.7  998.27  1245.4 1002.71  1315.2 1013.62    1365 1024.26
#Mann= 3 , 0 , 0
       0     .06       0  1029.6    .045       0  1074.6     .06       0
Bank Sta=1029.6,1074.6
XS Rating Curve= 0 ,0
Exp/Cntr=0.3,0.1

Type RM Length L Ch R = 1 ,23115   ,60.2,60.2,60.2
XS GIS Cut Line= 2
     1737808.624      435275.986     1738470.155         434082.
#Sta/Elev= 30
       0 1073.05    89.7 1070.36   209.2 1076.11   249.1 1073.62   318.8 1059.75
   338.8 1051.61   368.6 1031.87   388.6 1021.57   418.5 1010.18   448.4 1004.88
   617.7 1002.14   657.6  1003.9   667.6 1003.53   681.6  999.56   687.5  996.45
   707.4  994.71   717.1  997.44   727.3 1002.11   737.3 1003.62   777.2 1003.43
     817  998.28   846.9 1000.38   916.6 1000.23  1046.2 1007.45    1096 1017.46
  1135.8 1039.49  1175.7  1049.5  1255.4 1064.61  1325.2 1082.19    1365  1094.5
#Mann= 3 , 0 , 0
       0     .06       0   681.6    .045       0   717.1     .06       0
Bank Sta=681.6,717.1
XS Rating Curve= 0 ,0
Exp/Cntr=0.3,0.1

Type RM Length L Ch R = 1 ,23054.8 ,419.7,415.5,411.3
XS GIS Cut Line= 2
     1737861.107      435305.064     1738522.638      434111.079
#Sta/Elev= 30
       0 1084.55   179.3 1079.01   209.2 1081.96     269 1078.22   308.9 1072.25
   328.8 1065.68   358.7 1050.05   398.5 1022.44   438.4 1007.26   468.3 1004.11
   528.1 1001.92   657.6 1003.77   677.1  999.67   687.5  994.97   697.4  994.32
   707.4  994.32   715.5  997.09   727.3 1002.64   737.3 1003.87   787.1 1002.16
     817  996.67   836.9   999.1  1046.2 1006.68  1076.1 1013.02    1106 1025.74
  1135.8 1034.18  1195.6 1044.74  1235.5 1054.55  1305.2 1077.66    1365 1092.93
#Mann= 3 , 0 , 0
       0     .06       0   677.1    .045       0   715.5     .06       0
Bank Sta=677.1,715.5
XS Rating Curve= 0 ,0
Exp/Cntr=0.3,0.1

Type RM Length L Ch R = 1 ,22639.3 ,255.9,264.6,273.3
XS GIS Cut Line= 2
     1738428.495      435296.756     1738863.172      433991.926
#Sta/Elev= 30
       0 1097.69    69.8 1095.53   119.6 1091.63   199.3 1077.34   259.1 1061.12
     279 1053.15     299 1042.59   318.9 1024.61   358.8 1003.99   388.7 1001.52
   405.9  994.64   418.6  993.72   432.1  994.78   448.5  999.76   468.4  997.19
   528.2  999.32     588  995.89   627.9  996.01     867  1019.3     887 1019.59
   916.9 1024.36  1086.3 1069.28    1166 1094.62  1195.9 1108.13  1215.9 1120.29
  1235.8 1120.55  1285.6 1148.78  1345.4 1179.27  1355.4 1183.46  1375.3 1186.62
#Mann= 3 , 0 , 0
       0     .08       0   405.9    .045       0   432.1     .06       0
Bank Sta=405.9,432.1
XS Rating Curve= 0 ,0
Exp/Cntr=0.3,0.1

Type RM Length L Ch R = 1 ,22374.7 ,735.7,760.4,784.7
XS GIS Cut Line= 2
     1738578.764      435278.071     1739461.032      434223.021
#Sta/Elev= 30
       0 1065.52    69.8 1055.62   109.6 1047.92   179.4 1030.42   189.4 1027.26
   209.3  1017.5   219.3 1014.11   259.1 1014.62   269.1 1012.99     279 1010.04
     299 1000.65   327.4   994.6   348.8  992.86   365.3  994.17   378.7  996.36
   478.4  996.38   558.1 1003.24     877 1021.88     897 1025.76   976.7 1049.76
  1006.6 1056.08  1066.4  1063.8    1166  1072.4  1265.7 1077.13  1275.7 1075.56
  1305.6 1067.27  1325.5 1073.55  1335.5 1075.32  1345.4 1075.69  1375.3 1069.99
#Mann= 3 , 0 , 0
       0     .08       0   327.4    .045       0   365.3     .06       0
Bank Sta=327.4,365.3
XS Rating Curve= 0 ,0
Exp/Cntr=0.3,0.1