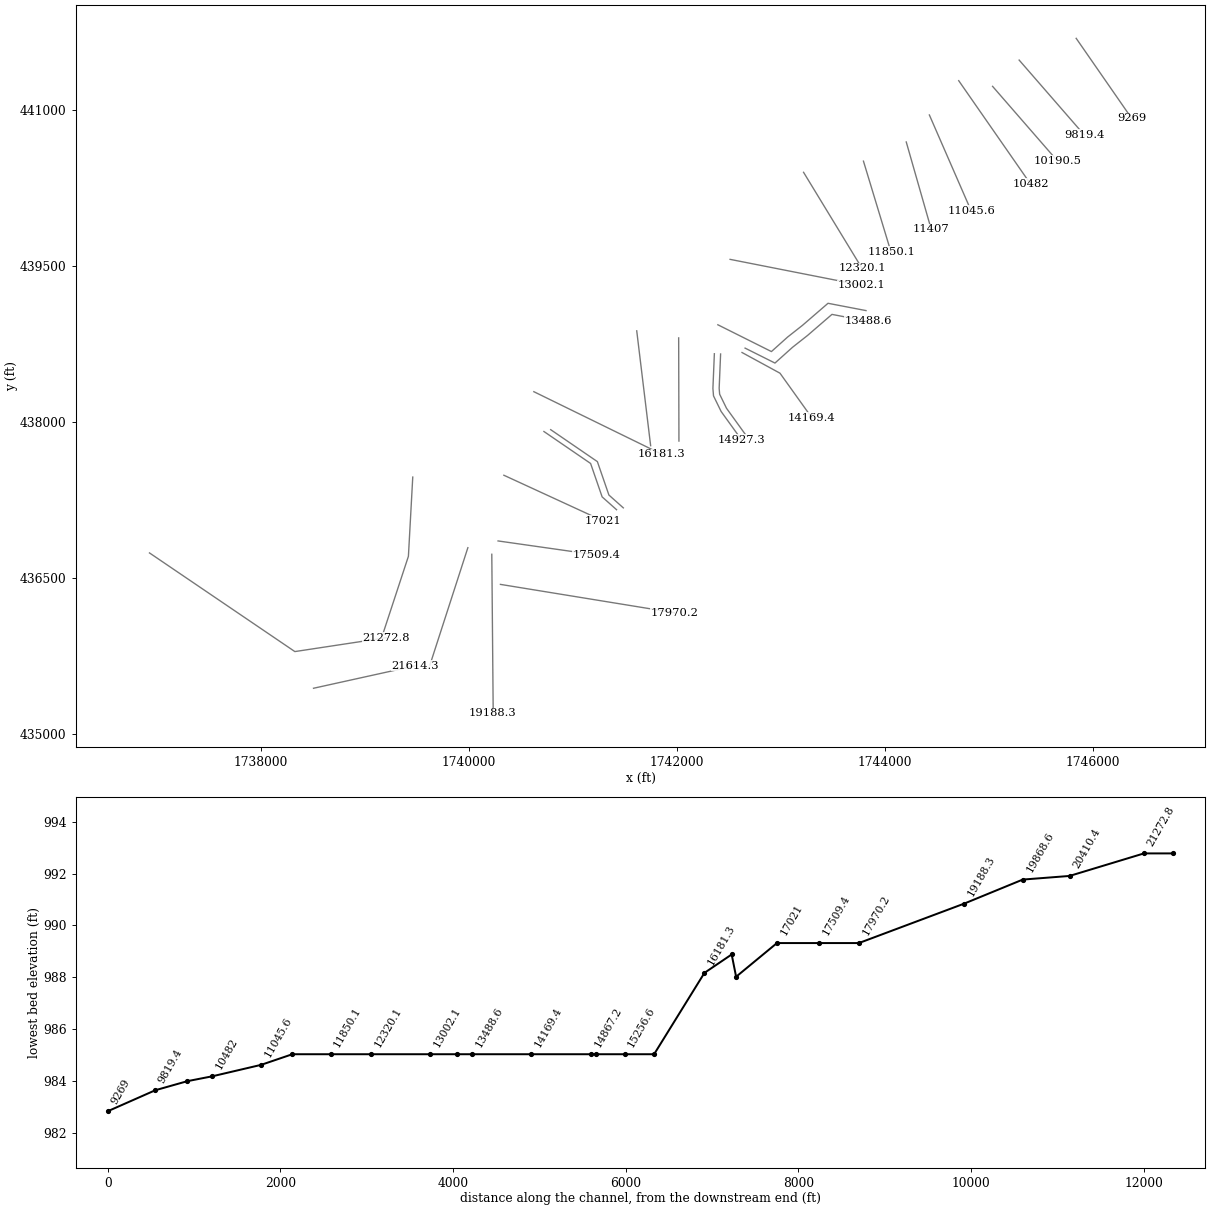
HEC-RAS study WestVaFork.prj: WestVaFork

--- WestVaFork.g01 (geometry) --- (continued)

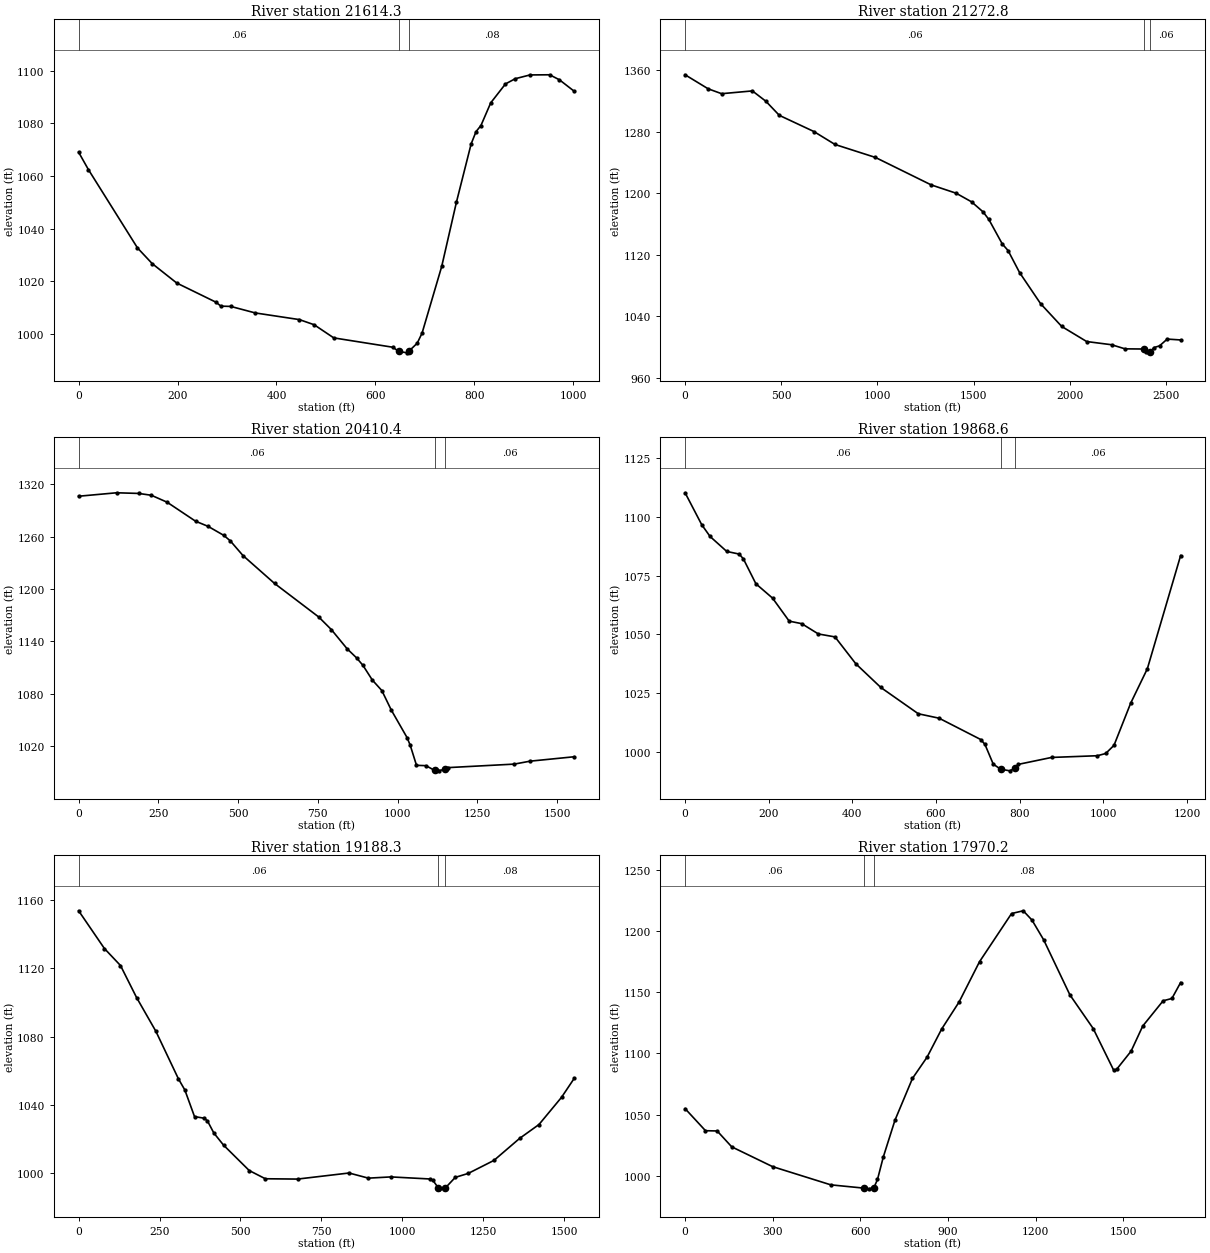
Type RM Length L Ch R = 1 ,21614.3 ,343.4,341.6,339.7
XS GIS Cut Line= 2
     1738506.823      435438.784     1739485.033      435654.708
#Sta/Elev= 30
       0 1069.01    19.8  1062.4     119 1032.64   148.8 1026.67   198.4  1019.3
   277.7 1012.02   287.6 1010.52   307.5 1010.42   357.1 1007.94   446.3 1005.41
   476.1 1003.46   515.8  998.46   634.8  994.92   647.7  993.29   664.5  992.78
   667.6   993.4   684.4  996.42   694.3 1000.27     734 1025.61   763.7 1049.98
   793.5 1072.17   803.4 1076.84   813.3 1079.15   833.1 1087.77   862.9 1094.96
   882.7 1096.95   912.5 1098.38   952.2 1098.44     972 1096.53  1001.8 1092.19
#Mann= 3 , 0 , 0
       0     .06       0   647.7    .045       0   667.6     .08       0
Bank Sta=647.7,667.6
XS Rating Curve= 0 ,0
Exp/Cntr=0.3,0.1

Type RM Length L Ch R = 1 ,21272.8 ,904.8,862.4,817.8
XS GIS Cut Line= 3
     1736930.183      436739.515       1738327.4      435791.314
     1739204.488      435924.411
#Sta/Elev= 30
       0 1353.69   119.9 1335.48   189.8 1329.14   349.7 1332.75   419.6 1319.39
   489.6 1301.05   669.4 1280.04   779.3 1263.21   989.2 1246.41  1278.9 1210.78
  1408.8 1199.96  1488.8  1188.8  1548.7 1175.76  1578.7 1165.96  1648.6 1134.12
  1678.6  1125.6  1738.4 1097.04  1848.1 1056.49  1957.7    1027  2087.3 1007.44
  2216.9 1003.29  2286.6  997.96  2387.5  997.74  2396.3  993.92  2416.2  992.78
    2418  993.33  2436.2  999.56  2466.1 1001.84  2505.9 1010.63  2575.7 1009.51
#Mann= 3 , 0 , 0
       0     .06       0  2387.5    .045       0    2418     .06       0
Bank Sta=2387.5,2418
XS Rating Curve= 0 ,0
Exp/Cntr=0.3,0.1

Type RM Length L Ch R = 1 ,20410.4 ,541.6,541.7,541.7
XS GIS Cut Line= 3
     1739460.565      437468.682     1739418.749      436707.144
     1739171.817      435955.896
#Sta/Elev= 30
       0 1306.07   118.9 1310.02   188.2 1309.27   227.8 1307.19   277.3 1299.25
   366.5 1277.51   406.1 1271.56   455.6 1261.18   475.4 1255.03   515.1 1238.25
   614.1 1206.33   752.8 1167.88   792.3  1153.5   841.8 1131.51   871.4 1121.13
   891.2 1112.64   920.8 1095.75   950.5 1083.78   980.2 1061.42  1029.6 1029.95
  1039.5 1021.22  1059.2  998.22  1088.9  997.82  1116.5   992.3  1128.4  991.91
  1149.2  993.97  1158.1   995.6  1365.7  999.61  1415.1 1002.97  1553.5 1008.02
#Mann= 3 , 0 , 0
       0     .06       0  1116.5    .045       0  1149.2     .06       0
Bank Sta=1116.5,1149.2
XS Rating Curve= 0 ,0
Exp/Cntr=0.3,0.1

Type RM Length L Ch R = 1 ,19868.6 ,672.7,680.4,687.8
XS GIS Cut Line= 2
     1739990.232       436789.87     1739625.635      435662.543
#Sta/Elev= 30
       0 1110.26    39.8 1096.64    59.7 1091.64    99.6 1085.26   129.4 1084.14
   139.4 1082.08   169.3 1071.48   209.1 1065.37   248.9 1055.56   278.8 1054.49
   318.6  1050.1   358.4 1048.84   408.2 1037.39     468 1027.29   557.6 1016.09
   607.3  1014.2   706.9 1005.11   716.9 1003.04   736.8  994.62   754.2  992.49
   776.6  991.77   788.3   992.9   796.5  994.52   876.2  997.48   985.7  998.21
  1005.6  999.16  1025.5 1002.65  1065.3 1020.58  1105.2 1035.27  1184.8 1083.52
#Mann= 3 , 0 , 0
       0     .06       0   754.2    .045       0   788.3     .06       0
Bank Sta=754.2,788.3
XS Rating Curve= 0 ,0
Exp/Cntr=0.3,0.1

Type RM Length L Ch R = 1 ,19188.3 ,1186.1,1218.1,1250
XS GIS Cut Line= 3
     1740220.174      436726.545     1740233.722      435204.921
     1740228.469      435197.364
#Sta/Elev= 30
       0 1153.82    79.6 1131.71   129.3 1121.74     179 1102.97   238.7 1083.16
   308.3 1055.31   328.2 1048.76     358 1033.18   387.9 1032.24   397.8 1030.72
   417.7 1023.57   447.6 1016.48   527.1 1001.56   576.8  996.75   676.3  996.56
   835.4 1000.12   895.1  997.11   964.7  997.83  1084.1  996.63    1094  995.94
  1110.6  991.57  1113.9  990.84  1131.9  991.16  1163.6  997.57  1203.4  999.86
    1283  1007.5  1362.6 1020.44  1422.2 1028.54  1491.8 1044.47  1530.9 1055.55
#Mann= 3 , 0 , 0
       0     .06       0  1110.6    .045       0  1131.9     .08       0
Bank Sta=1110.6,1131.9
XS Rating Curve= 0 ,0
Exp/Cntr=0.3,0.1

Type RM Length L Ch R = 1 ,17970.2 ,460.3,460.7,460.7
XS GIS Cut Line= 2
     1740303.171      436437.057     1741977.221      436164.513
#Sta/Elev= 30
       0 1054.88    69.8 1036.84   109.8 1036.63   159.6 1023.65   299.3 1007.49
   498.8  992.58   612.8  989.88   628.6  989.32   646.4  990.35   658.5  996.96
   678.4 1015.36   718.3 1045.41   778.2 1079.58   828.1 1096.91     878 1119.88
   937.8 1142.06  1007.7 1174.96  1117.4 1214.35  1157.3 1216.61  1187.3 1209.02
  1227.2  1192.9    1317 1147.89  1396.8 1120.35  1466.6 1086.43  1476.6 1086.89
  1526.5 1101.85  1566.4  1122.4  1636.2 1143.04  1666.2 1144.92  1696.1 1157.97
#Mann= 3 , 0 , 0
       0     .06       0   612.8    .045       0   646.4     .08       0
Bank Sta=612.8,646.4
XS Rating Curve= 0 ,0
Exp/Cntr=0.3,0.1

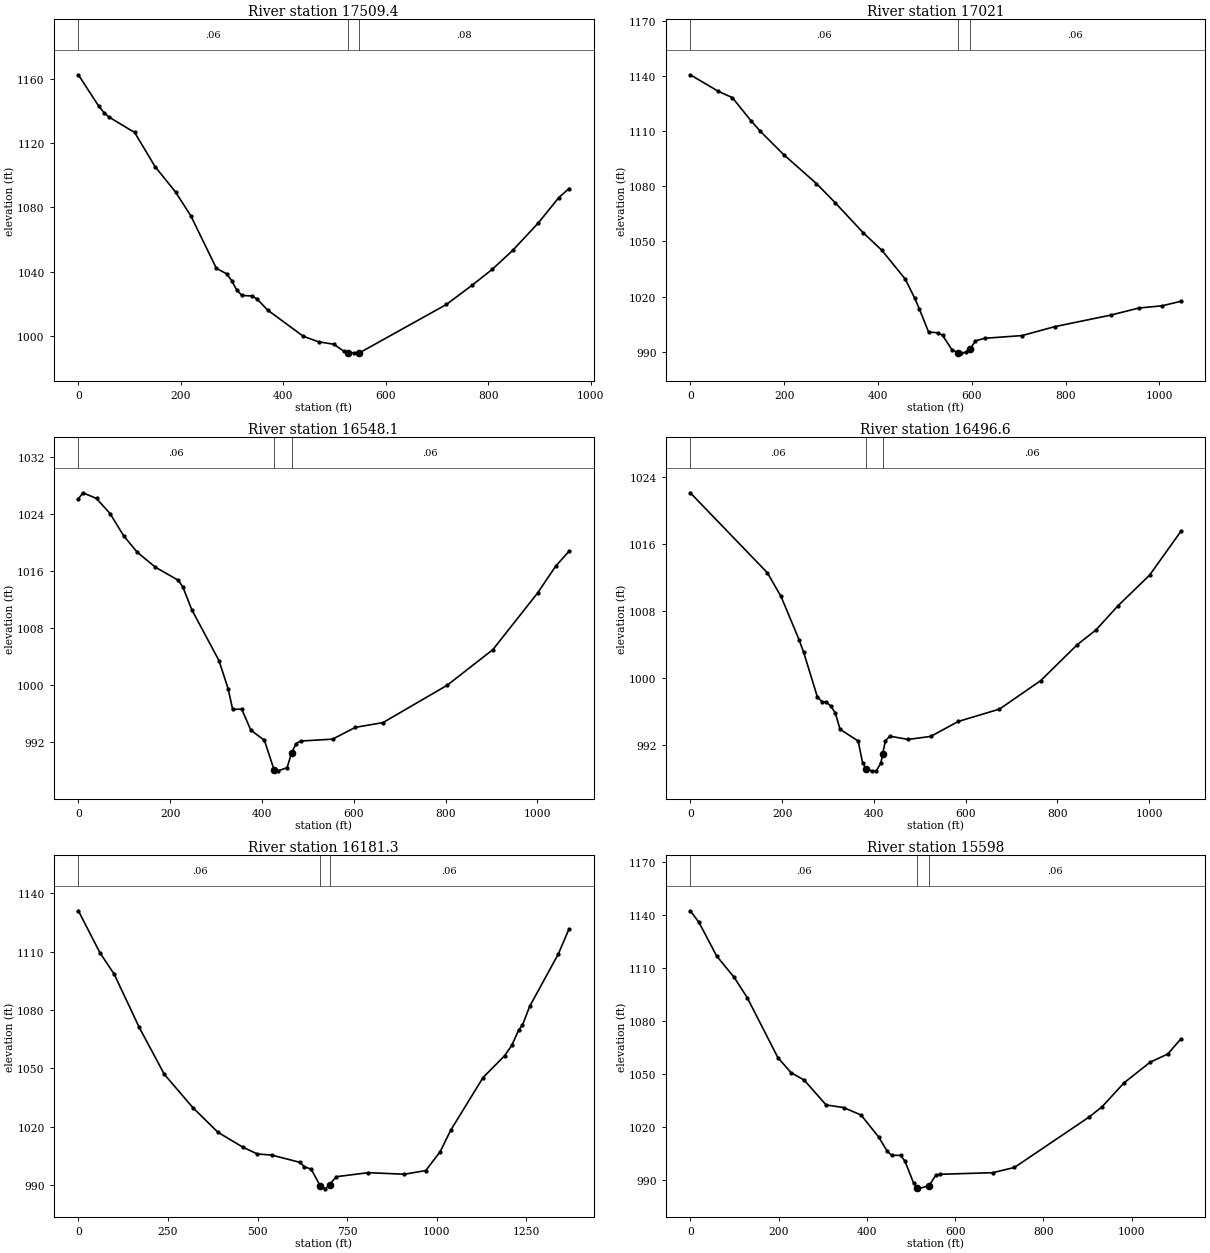
Type RM Length L Ch R = 1 ,17509.4 ,494.7,488.4,482.1
XS GIS Cut Line= 2
     1740280.413      436854.661     1741228.661      436719.626
#Sta/Elev= 30
       0 1162.76    39.9 1143.06    49.9 1139.23    59.9 1136.37   109.8 1126.77
   149.7 1105.47   189.6 1089.68   219.5 1074.79   269.4 1042.06   289.3 1038.64
   299.3 1034.36   309.3 1028.42   319.3 1025.15   339.2 1024.75   349.2 1022.79
   369.2 1016.07     439  999.66   468.9  996.21   498.9  994.67   518.8  990.16
   526.9  989.49   538.8  989.32   548.8  989.32   718.4 1019.48   768.2 1031.38
   808.2 1041.47   848.1 1053.28     898 1070.39   937.9 1086.15   957.8 1091.77
#Mann= 3 , 0 , 0
       0     .06       0   526.9    .045       0   548.8     .08       0
Bank Sta=526.9,548.8
XS Rating Curve= 0 ,0
Exp/Cntr=0.3,0.1

Type RM Length L Ch R = 1 ,17021   ,476.7,472.9,469.1
XS GIS Cut Line= 2
     1740336.252      437486.071     1741286.034       437048.81
#Sta/Elev= 30
       0 1140.79    59.8 1131.78    89.6 1128.35   129.5 1115.73   149.4 1109.97
   199.2 1097.28   268.9 1081.53   308.7 1071.14   368.4 1054.78   408.3  1045.2
   458.1 1029.52     478 1019.26     488 1013.36   507.9 1000.66   527.8 1000.25
   537.7  998.83   557.6  991.06   569.8  989.42   577.6  989.32   587.5  989.54
   595.1   991.2   597.5  991.73   607.4  995.81   627.4  997.24     707  998.72
   776.7 1003.58   896.2 1009.88     956 1013.72  1005.8 1014.96  1045.6  1017.4
#Mann= 3 , 0 , 0
       0     .06       0   569.8    .045       0   595.1     .06       0
Bank Sta=569.8,595.1
XS Rating Curve= 0 ,0
Exp/Cntr=0.3,0.1

Type RM Length L Ch R = 1 ,16548.1 ,51.5,51.5,51.4
XS GIS Cut Line= 4
     1740721.184       437906.46     1741169.841      437599.352
     1741280.578      437278.187     1741419.166      437154.857
#Sta/Elev= 30
       0 1026.15     9.9    1027    39.5  1026.2    69.2 1024.07    98.8 1020.95
   128.5 1018.65     168 1016.56   217.5 1014.74   227.4 1013.83   247.1  1010.6
   306.4 1003.46   326.2  999.54   336.1  996.64   355.9  996.67   375.6  993.73
   405.3   992.3   426.2  988.19     435  988.02   454.7  988.46   464.4  990.51
   474.5  991.85   484.4   992.2   553.7  992.46   603.6  994.12   663.6  994.78
   803.5 1000.02     903 1005.01  1000.6 1012.96  1039.6 1016.69  1068.9  1018.8
#Mann= 3 , 0 , 0
       0     .06       0   426.2    .045       0   464.4     .06       0
Bank Sta=426.2,464.4
XS Rating Curve= 0 ,0
Exp/Cntr=0.3,0.1

Type RM Length L Ch R = 1 ,16496.6 ,312,315.3,318.8
XS GIS Cut Line= 4
     1740786.333      437924.105      1741234.99      437616.997
     1741345.728      437295.832     1741484.315      437172.501
#Sta/Elev= 30
       0 1022.17     168 1012.59   197.7 1009.76   237.2 1004.56   247.1 1003.06
   276.8  997.75   286.7  997.17   296.6  997.11   306.4  996.62   316.3  995.77
   326.2  993.86   365.8  992.45   375.6  989.79   383.4   989.1   395.4  988.88
   405.3  988.88   415.2  989.82     419  990.84   425.1  992.48     435  993.03
   474.5  992.64   523.9     993   583.7  994.79   673.6  996.27   763.5  999.68
   843.4    1004   883.4 1005.72   932.2 1008.66  1000.6  1012.3  1068.9 1017.55
#Mann= 3 , 0 , 0
       0     .06       0   383.4    .045       0     419     .06       0
Bank Sta=383.4,419
XS Rating Curve= 0 ,0
Exp/Cntr=0.3,0.1

Type RM Length L Ch R = 1 ,16181.3 ,605.7,583.3,560.5
XS GIS Cut Line= 2
     1740624.342      438289.126     1741854.047      437687.801
#Sta/Elev= 30
       0 1130.98      60 1109.45    99.9 1098.42   169.9 1071.04   239.8 1046.99
   319.7 1029.81   389.7 1017.18   459.6  1009.5   499.6 1006.07   539.6 1005.51
   619.5 1001.71   629.5   999.6   649.5  998.24   675.5  989.47   689.4  988.17
   700.8  990.35   719.4   994.4   809.3  996.48   909.2  995.67   969.2  997.55
  1009.2 1007.18  1039.1 1018.35  1129.1 1045.33    1189  1056.5    1209  1061.8
    1229 1069.89    1239 1072.17    1259 1081.84  1338.9 1108.71  1368.9 1121.61
#Mann= 3 , 0 , 0
       0     .06       0   675.5    .045       0   700.8     .06       0
Bank Sta=675.5,700.8
XS Rating Curve= 0 ,0
Exp/Cntr=0.3,0.1

Type RM Length L Ch R = 1 ,15598   ,344.1,341.4,338.8
XS GIS Cut Line= 2
      1741613.16      438873.925     1741746.863      437770.376
#Sta/Elev= 30
       0 1142.52    19.8 1135.91    59.6 1116.98    99.2 1104.89     129 1093.34
   198.5 1059.35   228.3 1050.84     258 1046.65   307.7 1032.56   347.4 1031.07
   387.1 1026.82   426.8 1014.38   446.6 1006.18   456.6 1004.03   476.4    1004
   486.3 1000.78   506.2  988.18   514.6  985.51   516.1  985.03   541.1  986.86
   555.8  992.59   565.7  993.28   684.8  994.16   734.5  997.14   903.2 1025.62
     933  1031.5   982.6 1045.02  1042.1 1056.77  1081.8 1061.38  1111.6 1069.96
#Mann= 3 , 0 , 0
       0     .06       0   514.6    .045       0   541.1     .06       0
Bank Sta=514.6,541.1
XS Rating Curve= 0 ,0
Exp/Cntr=0.3,0.1

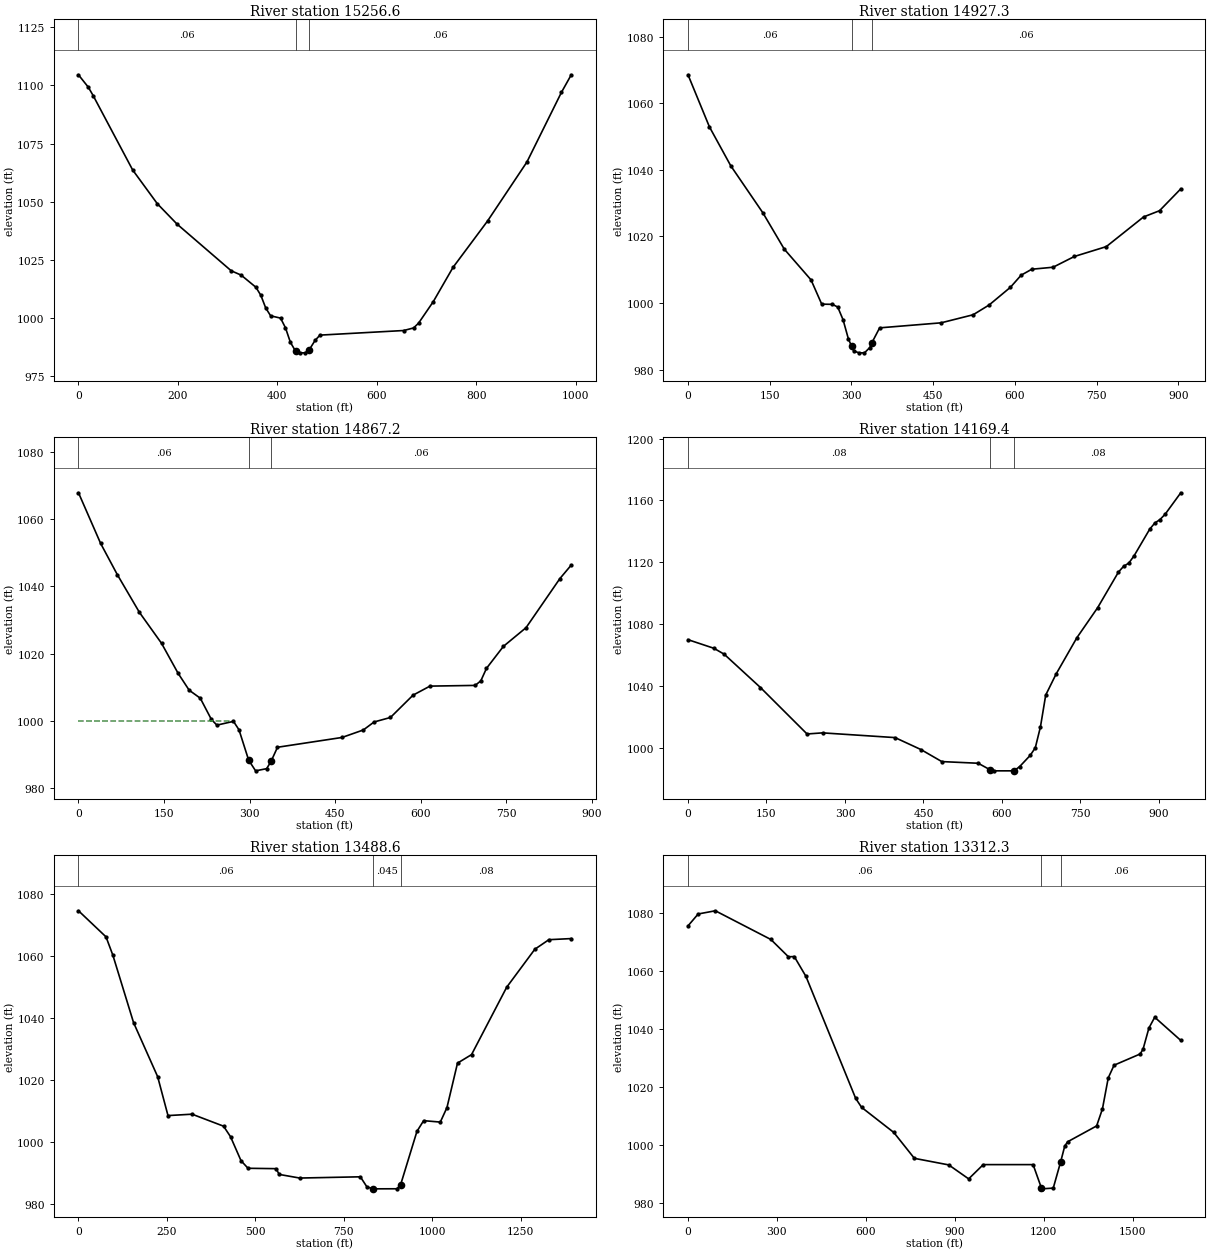
Type RM Length L Ch R = 1 ,15256.6 ,330.3,329.3,329.1
XS GIS Cut Line= 2
     1742016.204      438806.071     1742018.834      437814.677
#Sta/Elev= 30
       0 1104.57    19.8 1099.26    29.7 1095.58     109 1063.67   158.6 1049.16
   198.3 1040.39   307.3 1020.31   327.2 1018.46   356.9 1013.24   366.8  1009.8
   376.7 1004.31   386.6 1000.94   406.5  999.97   416.4  995.81   426.3  989.57
     437  985.64   446.1  985.03     456  985.03   464.3  986.38   475.9  990.35
   485.8  992.65   654.3  994.63   674.2  995.74   684.1  997.77   713.8 1007.05
   753.5 1021.78   822.9  1041.7   902.2  1067.1   971.6 1097.04   991.4 1104.61
#Mann= 3 , 0 , 0
       0     .06       0     437    .045       0   464.3     .06       0
Bank Sta=437,464.3
XS Rating Curve= 0 ,0
Exp/Cntr=0.3,0.1

Type RM Length L Ch R = 1 ,14927.3 ,60.1,60.1,61
XS GIS Cut Line= 5
      1742359.33      438653.944     1742345.364      438320.505
     1742351.178       438248.79     1742424.229      438099.035
     1742618.438      437829.592
#Sta/Elev= 30
       0 1068.51    39.3 1052.88    78.5 1041.18   137.4 1027.07   176.7 1016.16
   225.8 1006.93   245.4  999.65     265  999.59   274.8  998.78   284.6  994.96
   294.5  989.14   300.1  987.09   304.3  985.56   314.1  985.03   323.9  985.03
   333.7  986.63   337.4  988.04   351.7  992.53   464.5  994.04   523.3  996.46
   552.7   999.4   591.8 1004.72   611.4 1008.34   630.9 1010.13     670 1010.73
   709.1 1013.96   767.7 1016.92   836.1 1025.83   865.4  1027.7   904.4 1034.26
#Mann= 3 , 0 , 0
       0     .06       0   300.1    .045       0   337.4     .06       0
#XS Ineff= 2 , 0
          263.95  999.39
Permanent Ineff=
       F       F
Bank Sta=300.1,337.4
XS Rating Curve= 0 ,0
Exp/Cntr=0.3,0.1

Type RM Length L Ch R = 1 ,14867.2 ,682.8,697.8,711.1
XS GIS Cut Line= 5
     1742419.277      438651.433     1742405.465      438321.678
     1742410.067      438264.921     1742475.905      438129.954
     1742667.113      437864.675
#Sta/Elev= 30
       0 1067.93    38.8 1052.84      68 1043.55   106.8 1032.29   145.6 1023.06
   174.7 1014.11   194.1 1009.07   213.6 1006.68     233 1000.37   242.7  998.66
   271.8  999.78   281.5  997.26   298.4  988.23   310.6  985.03     330  985.68
   337.8  987.89     349  992.06   462.1  994.98   499.6  997.22   518.4   999.6
   547.1 1000.94   586.7 1007.59   616.4 1010.29   695.7  1010.5   705.6 1011.87
   715.5 1015.58   745.2 1022.14   784.9 1027.71   844.3 1042.36   864.2 1046.38
#Mann= 3 , 0 , 0
       0     .06       0   298.4    .045       0   337.8     .06       0
#XS Ineff= 2 , 0
          264.84   999.9
Permanent Ineff=
       F       F
Bank Sta=298.4,337.8
XS Rating Curve= 0 ,0
Exp/Cntr=0.3,0.1

Type RM Length L Ch R = 1 ,14169.4 ,632.6,680.8,728.5
XS GIS Cut Line= 3
     1742625.144      438665.606     1742989.998      438466.925
     1743296.222      438038.888
#Sta/Elev= 30
       0 1069.91    49.5 1064.33    69.2 1060.49   138.5 1038.93   227.5 1008.88
   257.2  1009.6   395.7 1006.54   445.2  998.79     485  991.02   554.5  989.94
   577.4   985.7   584.3  985.03   623.1  985.03   633.9  987.82   653.8  994.97
   663.7  999.96   673.6 1013.62   683.6 1034.07   703.4 1047.66   743.1 1071.14
   782.9 1090.64   822.6 1113.65   832.5 1117.39   842.4 1119.46   852.4 1124.14
   882.2 1141.34   892.1  1145.4     902 1147.64     912 1151.16   941.7 1164.96
#Mann= 3 , 0 , 0
       0     .08       0   577.4    .045       0   623.1     .08       0
Bank Sta=577.4,623.1
XS Rating Curve= 0 ,0
Exp/Cntr=0.3,0.1

Type RM Length L Ch R = 1 ,13488.6 ,178.4,176.3,174.7
XS GIS Cut Line= 6
     1742654.582      438707.924     1742941.764      438564.333
     1743111.035      438716.243     1743254.264       438829.09
      1743489.48      439032.116     1743834.546      438966.035
#Sta/Elev= 30
       0 1074.46    77.8 1066.07    97.3 1060.13   155.7 1038.48   223.8  1021.1
     253 1008.59   321.1 1009.04   410.1 1005.18   429.8 1001.79   459.5  994.07
   479.3  991.64   558.1  991.52   567.7  989.66   625.3   988.5   796.8   988.9
   815.6  985.61   832.5  985.09   834.4  985.03   900.3  985.05   910.5  986.32
   956.8 1003.53   975.7 1006.96  1022.8  1006.5  1041.6 1011.16  1071.4 1025.46
  1111.1  1028.2  1210.5 1049.88    1290 1062.09  1329.7 1065.16    1393 1065.52
#Mann= 3 , 0 , 0
       0     .06       0   832.5    .045       0   910.5     .08       0
Bank Sta=832.5,910.5
XS Rating Curve= 0 ,0
Exp/Cntr=0.3,0.1

Type RM Length L Ch R = 1 ,13312.3 ,340,310.2,280.1
XS GIS Cut Line= 6
     1742392.997      438932.235      1742907.84      438674.814
     1743062.633       438813.73     1743206.131      438926.789
     1743451.605      439138.742     1743816.934        439068.6
#Sta/Elev= 30
       0 1075.55    34.3 1079.65    92.2 1080.75   279.6 1070.87   338.8 1064.92
   358.6 1064.99     398 1058.15   565.8 1016.16   585.5  1013.1   694.5 1004.43
   763.8  995.53   879.8  993.27     947  988.46   996.2  993.37  1164.4  993.37
  1192.2   985.4  1193.6  985.03  1232.4  985.28  1257.2  994.26  1271.2  999.76
  1280.9 1001.23  1378.8 1006.69  1398.4 1012.56    1418 1023.24  1437.6 1027.59
  1525.8 1031.46  1535.6 1033.16  1555.2 1040.39  1574.8  1044.1  1662.7 1036.12
#Mann= 3 , 0 , 0
       0     .06       0  1192.2    .045       0  1257.2     .06       0
Bank Sta=1192.2,1257.2
XS Rating Curve= 0 ,0
Exp/Cntr=0.3,0.1

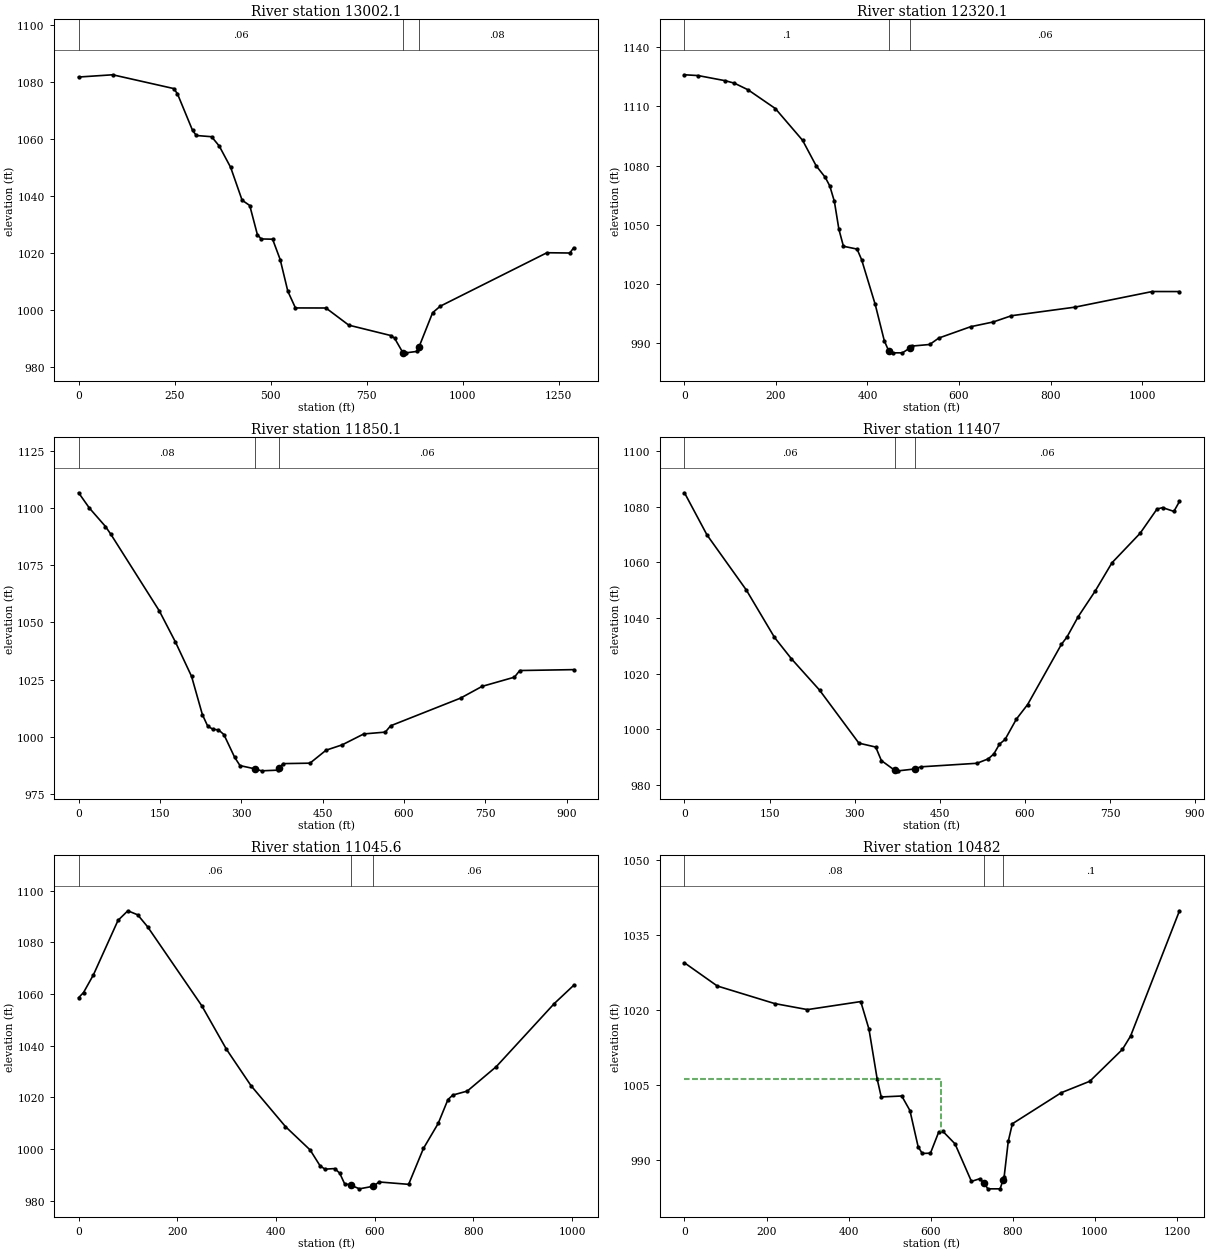
Type RM Length L Ch R = 1 ,13002.1 ,700,682,664.3
XS GIS Cut Line= 3
     1742510.406      439560.976      1742675.07      439528.537
     1743775.169      439311.818
#Sta/Elev= 30
       0 1081.65    88.8 1082.44   247.2 1077.63   257.1 1075.88   296.8 1062.94
   306.7 1061.17   346.4 1060.74   366.3 1057.47     396 1049.99   425.8  1038.5
   445.7 1036.64   465.5 1026.48   475.4 1024.93   505.2 1024.84     525 1017.69
   544.9 1006.59   564.7 1000.76   644.1 1000.74   703.6  994.73   812.8   991.1
   822.7   990.2   844.6  985.06   852.5  985.03   882.2  985.55   886.9  987.23
   921.9  999.08   941.8 1001.37  1219.6  1020.1  1279.2    1020  1289.1 1021.82
#Mann= 3 , 0 , 0
       0     .06       0   844.6    .045       0   886.9     .08       0
Bank Sta=844.6,886.9
XS Rating Curve= 0 ,0
Exp/Cntr=0.3,0.1

Type RM Length L Ch R = 1 ,12320.1 ,475.7,470,464.2
XS GIS Cut Line= 2
     1743216.643      440397.663     1743779.291      439473.557
#Sta/Elev= 30
       0 1126.07    29.8 1125.67    89.3 1123.05   109.2  1121.8     139 1118.44
   198.5 1108.96   258.1 1092.84   287.8  1079.9   307.7 1074.04   317.6 1069.66
   327.6 1061.86   337.5 1047.69   347.4 1039.09   377.2 1037.66   387.1 1032.31
   416.9 1009.56   436.7   991.2   446.9  985.71   456.6  985.03   476.4  985.03
   491.9  987.39   496.3  988.44     536  989.27   555.8  992.53   625.3  998.27
     675  1000.7   714.7 1003.86   853.6 1008.21  1022.4 1016.13  1081.9 1016.11
#Mann= 3 , 0 , 0
       0      .1       0   446.9    .045       0   491.9     .06       0
Bank Sta=446.9,491.9
XS Rating Curve= 0 ,0
Exp/Cntr=0.3,0.1

Type RM Length L Ch R = 1 ,11850.1 ,443.5,443.1,442.8
XS GIS Cut Line= 2
      1743792.26      440504.981     1744057.083       439631.17
#Sta/Elev= 30
       0  1106.8    19.8 1100.13    49.6 1092.03    59.6 1088.58   148.9 1055.07
   178.6 1041.46   208.4 1026.38   228.3 1009.67   238.2 1004.58   248.1 1003.21
     258 1002.98     268 1000.92   287.8  990.97   297.7  987.33   324.6  985.93
   337.4  985.03   367.2  985.33   370.4  986.25   377.1  988.19   426.8  988.39
   456.5  994.07   486.3  996.42     526 1001.19   565.7 1001.99   575.6 1004.76
   704.6 1016.88   744.3 1022.02   803.9 1026.05   813.8 1028.96   913.1 1029.35
#Mann= 3 , 0 , 0
       0     .08       0   324.6    .045       0   370.4     .06       0
Bank Sta=324.6,370.4
XS Rating Curve= 0 ,0
Exp/Cntr=0.3,0.1

Type RM Length L Ch R = 1 ,11407   ,358.4,361.4,364.5
XS GIS Cut Line= 2
     1744203.551      440689.209     1744443.374      439850.342
#Sta/Elev= 30
       0 1085.03    39.7 1069.86   109.1 1050.03   158.6 1033.04   188.4 1025.35
     238 1014.08   307.4  994.99   337.1  993.58     347  988.73   370.2  985.28
   376.8  985.03   405.7   985.7   416.4  986.47   515.6  987.75   535.4  989.34
   545.3  991.11   555.2  994.63   565.1  996.32     585 1003.63   604.8 1008.86
   664.3 1030.49   674.2 1033.16     694 1040.49   723.8 1049.65   753.5 1059.85
   803.1 1070.46   832.8 1079.16   842.7  1079.7   862.6 1078.33   872.5 1081.92
#Mann= 3 , 0 , 0
       0     .06       0   370.2    .045       0   405.7     .06       0
Bank Sta=370.2,405.7
XS Rating Curve= 0 ,0
Exp/Cntr=0.3,0.1

Type RM Length L Ch R = 1 ,11045.6 ,559,563.6,568
XS GIS Cut Line= 3
     1744425.786      440948.766     1744721.028      440271.493
     1744826.708      440029.068
#Sta/Elev= 30
       0  1058.6      10  1060.6      30 1067.44    79.9 1088.53    99.8 1092.24
   119.8 1090.67   139.8 1086.06   249.6  1055.5   299.5 1038.69   349.4 1024.56
   419.3 1008.71   469.3  999.66   489.2   993.6   499.2  992.23   519.2  992.47
   529.2  990.68   539.1  986.61   551.3   986.1   569.1  984.62   597.3  985.62
     609  987.28   668.9  986.36   698.9 1000.25   728.8 1009.92   748.6 1019.17
   758.4 1020.91   787.8 1022.46   846.6 1031.92   964.1 1056.33  1003.3 1063.36
#Mann= 3 , 0 , 0
       0     .06       0   551.3    .045       0   597.3     .06       0
Bank Sta=551.3,597.3
XS Rating Curve= 0 ,0
Exp/Cntr=0.3,0.1

Type RM Length L Ch R = 1 ,10482   ,289.1,291.5,294
XS GIS Cut Line= 3
     1744707.836      441278.184     1745141.255      440654.818
     1745396.462      440287.767
#Sta/Elev= 30
       0 1029.44    79.9  1024.8   219.8 1021.28   299.7 1020.07   429.6 1021.68
   449.6 1016.15   469.5 1006.21   479.5 1002.58   529.5 1002.77   549.4  999.86
   569.4  992.61   579.4  991.27   599.4  991.32   619.4  995.52   629.4  995.72
   659.3  993.19   699.3  985.67   719.3   986.2   731.1  985.25   739.2  984.18
   769.2  984.18   776.4  985.98   779.1  986.65     789  993.68     799  997.21
   918.2 1003.43   987.7 1005.72  1067.2  1012.1  1087.1 1014.77  1206.3 1039.86
#Mann= 3 , 0 , 0
       0     .08       0   731.1    .045       0   776.4      .1       0
#XS Ineff= 2 , 0
          625.26 1006.13
Permanent Ineff=
       F       F
Bank Sta=731.1,776.4
XS Rating Curve= 0 ,0
Exp/Cntr=0.3,0.1

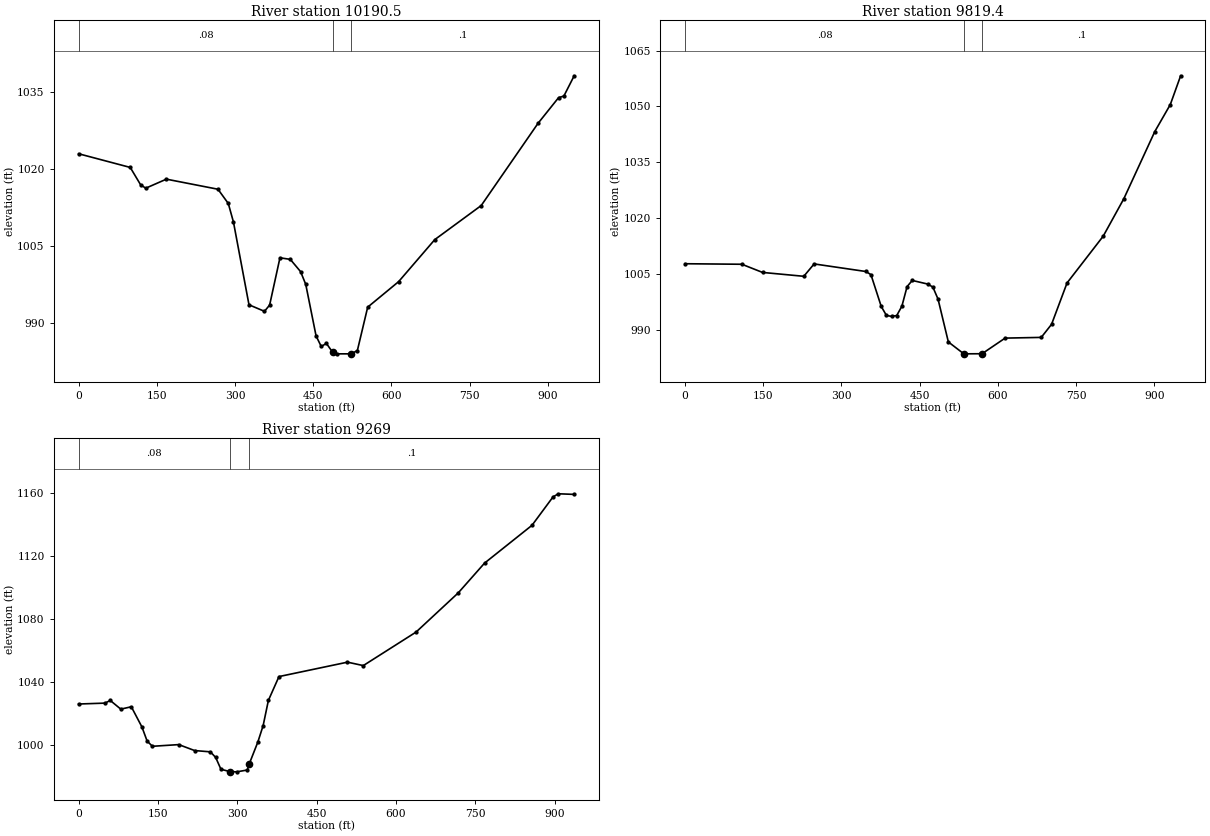
Type RM Length L Ch R = 1 ,10190.5 ,370.6,371.1,371.6
XS GIS Cut Line= 2
     1745033.366      441223.739     1745657.191      440506.533
#Sta/Elev= 30
       0 1022.91      99 1020.25   118.8 1016.89   128.7 1016.21   168.3 1017.97
   267.3 1016.01   287.1 1013.24     297 1009.63   326.8  993.53   356.5  992.26
   366.4  993.48   386.2 1002.67     406 1002.37   425.8  999.98   435.7   997.5
   455.5  987.47   465.4  985.42   475.3  986.02   487.2   984.3   495.1  983.99
   522.7  983.99   534.7  984.63   554.5  993.07   613.9  998.04   683.2 1006.21
   772.3 1012.84   881.2 1028.82   920.8 1033.84   930.8 1034.13   950.6 1038.08
#Mann= 3 , 0 , 0
       0     .08       0   487.2    .045       0   522.7      .1       0
#XS Ineff= 2 , 0
          400.41 1001.94
Permanent Ineff=
       F       F
Bank Sta=487.2,522.7
XS Rating Curve= 0 ,0
Exp/Cntr=0.3,0.1

Type RM Length L Ch R = 1 ,9819.4  ,553.2,550.4,547.5
XS GIS Cut Line= 2
     1745288.574      441476.343     1745912.399      440759.137
#Sta/Elev= 30
       0 1007.81   108.9 1007.67   148.5 1005.48   227.7 1004.44   247.5 1007.76
   346.6 1005.73   356.5 1004.89   376.3  996.34   386.2  993.95   396.1  993.68
     406  993.92   415.9  996.43   425.8 1001.66   435.7 1003.33   465.4 1002.36
   475.3 1001.55   485.2  998.33     505  986.83   534.7  983.64   535.8  983.64
   569.7  983.67   613.9  987.86   683.2  988.05     703  991.56   732.7 1002.66
     802 1015.19   841.6 1025.24     901 1043.26   930.8 1050.52   950.6 1058.23
#Mann= 3 , 0 , 0
       0     .08       0   535.8    .045       0   569.7      .1       0
#XS Ineff= 2 , 0
          450.72  1002.8
Permanent Ineff=
       F       F
Bank Sta=535.8,569.7
XS Rating Curve= 0 ,0
Exp/Cntr=0.3,0.1

Type RM Length L Ch R = 1 ,9269    ,351.5,351.5,351.5
XS GIS Cut Line= 2
     1745836.816      441685.278      1746370.62      440915.575
#Sta/Elev= 30
       0 1025.99    49.8 1026.56    59.8 1028.25    79.7 1022.73    99.6 1024.24
   119.6 1011.42   129.5 1002.39   139.5  999.09   189.3 1000.16   219.2  996.38
   249.1  995.55   259.1  991.96     269  984.47   285.9  982.97   298.9  982.83
   318.9  983.99   322.6  987.95   338.8 1001.82   348.8  1012.3   358.7  1028.3
   378.7 1043.45   508.2 1052.62   538.1 1050.44   637.8 1071.76   717.5 1096.68
   767.3 1115.65     857 1139.71   896.8  1157.8   906.8 1159.77   936.7 1159.38
#Mann= 3 , 0 , 0
       0     .08       0   285.9    .045       0   322.6      .1       0
Bank Sta=285.9,322.6
XS Rating Curve= 0 ,0
Exp/Cntr=0.3,0.1