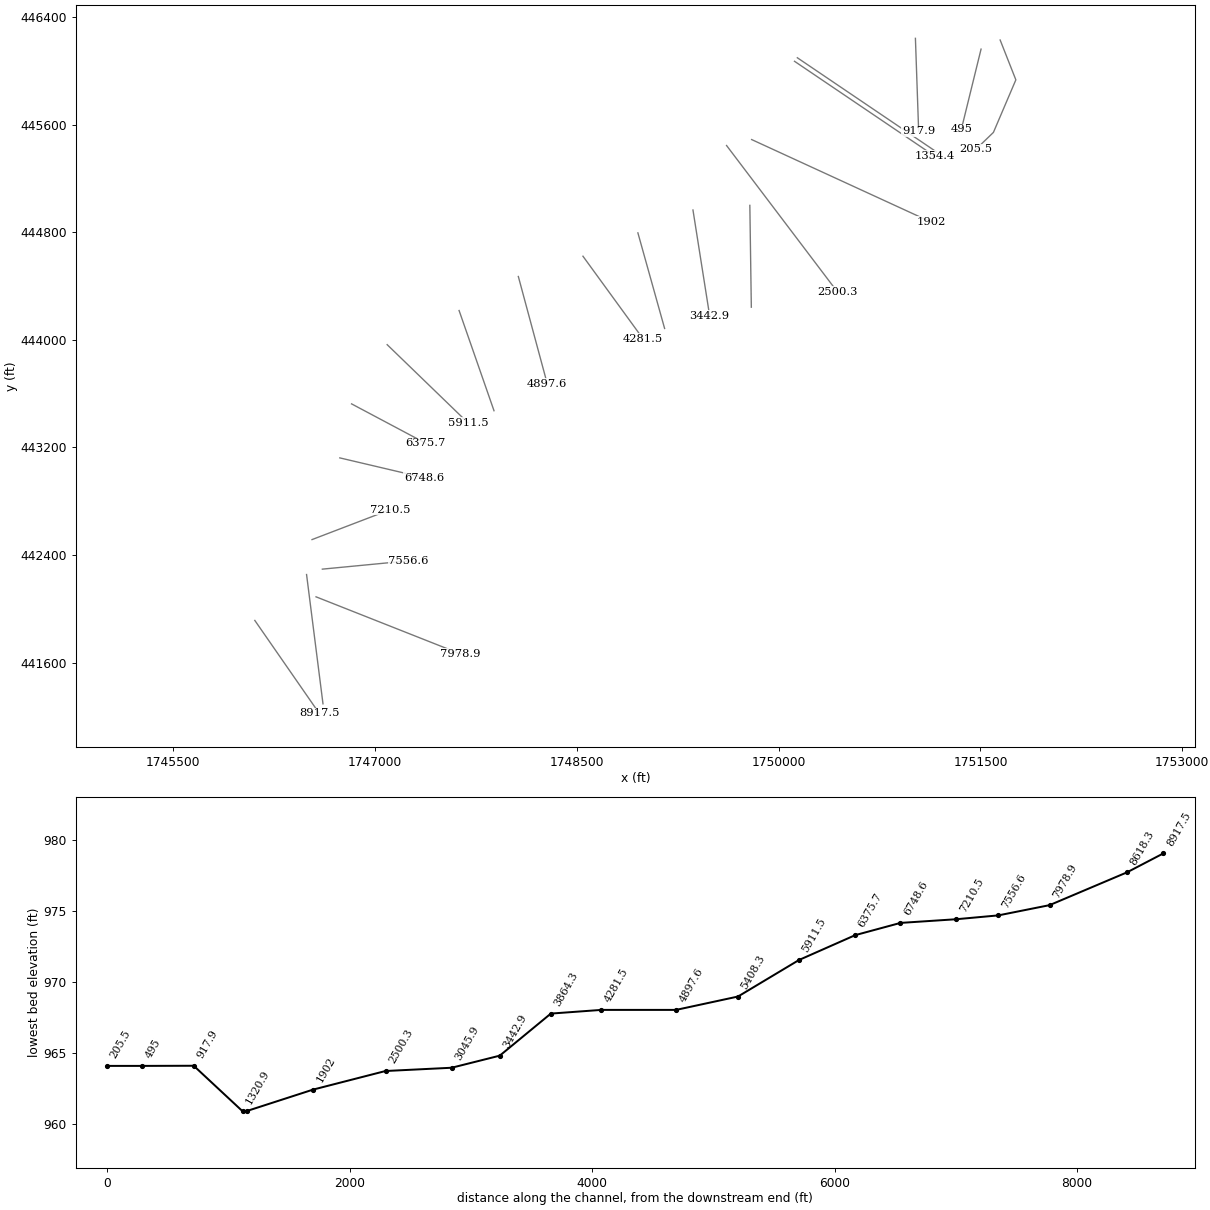
HEC-RAS study WestVaFork.prj: WestVaFork

--- WestVaFork.g01 (geometry) --- (continued)

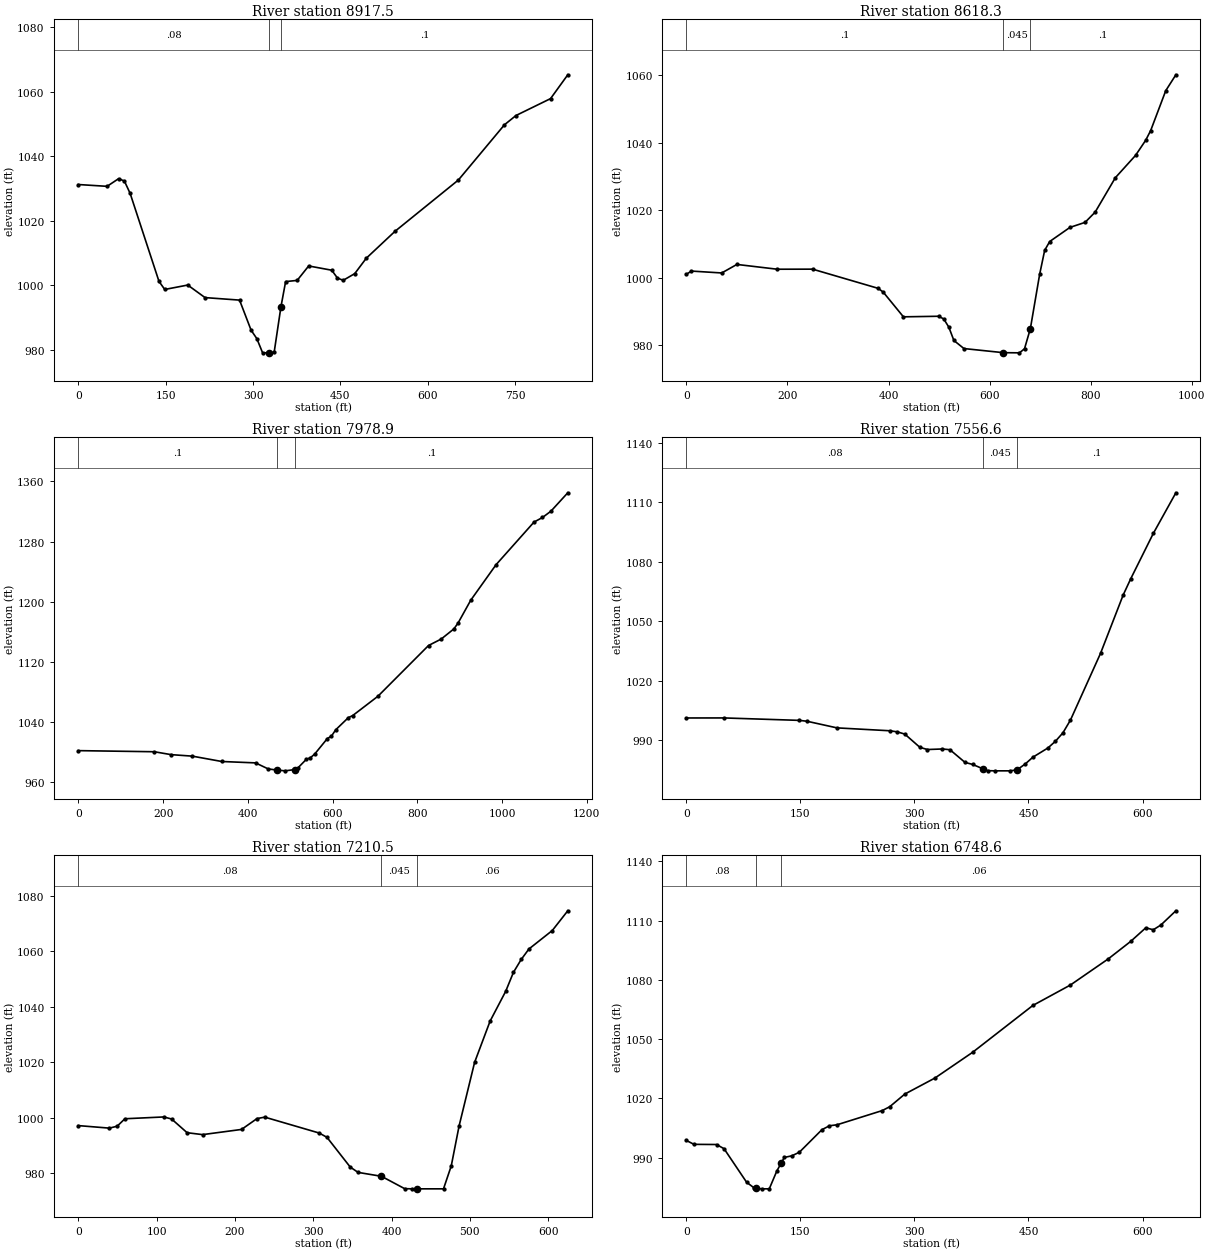
Type RM Length L Ch R = 1 ,8917.5  ,309,299.2,290
XS GIS Cut Line= 2
     1746105.959      441913.895     1746585.026      441223.119
#Sta/Elev= 30
       0 1031.24    49.4 1030.68    69.2 1033.06    79.1 1032.32      89 1028.48
   138.5 1001.22   148.4   998.7   187.9 1000.07   217.6  996.18   276.9   995.4
   296.7  986.08   306.6  983.44   316.5  979.05   326.9  979.06   336.3  979.19
   347.9  993.25     356 1001.14   375.8 1001.51   395.6 1005.99   435.2 1004.67
     445 1002.24   454.9 1001.54   474.7 1003.61   494.5 1008.38   543.9 1016.74
   652.7 1032.64   731.8 1049.76   751.6 1052.64     811 1057.88   840.6 1065.27
#Mann= 3 , 0 , 0
       0     .08       0   326.9    .045       0   347.9      .1       0
Bank Sta=326.9,347.9
XS Rating Curve= 0 ,0
Exp/Cntr=0.3,0.1

Type RM Length L Ch R = 1 ,8618.3  ,616.4,639.4,661.9
XS GIS Cut Line= 2
     1746490.584      442255.269     1746612.712      441294.168
#Sta/Elev= 30
       0 1001.03      10 1001.97    69.9 1001.41    99.9 1003.94   179.8 1002.52
   249.7 1002.54   379.5  996.85   389.5  995.74   429.5   988.4   499.4  988.57
   509.4  987.76   519.4  985.34   529.4  981.39   549.3  978.99   627.4  977.77
   659.2  977.72   669.2  978.93   680.8  984.91   699.2 1001.04   709.1 1008.12
   719.1 1010.74   759.1 1014.92     789 1016.41     809 1019.45     849 1029.66
   888.9 1036.27   908.9 1040.73   918.9 1043.64   948.8 1055.49   968.8 1060.19
#Mann= 3 , 0 , 0
       0      .1       0   627.4    .045       0   680.8      .1       0
Bank Sta=627.4,680.8
XS Rating Curve= 0 ,0
Exp/Cntr=0.3,0.1

Type RM Length L Ch R = 1 ,7978.9  ,411.5,422.3,432.9
XS GIS Cut Line= 2
     1746560.958      442089.489     1747635.057      441664.835
#Sta/Elev= 30
       0 1002.25   179.2 1000.78     219  996.93   268.8  994.95   338.5  987.82
   418.2  985.97   448.1  977.95   469.1  976.41   487.9  975.41   511.2  977.11
   517.8  979.09   537.7  990.54   547.6  992.79   557.6   997.6   587.5 1018.25
   597.4 1021.64   607.4 1029.96   637.2 1046.12   647.2 1048.74   706.9 1074.47
   826.4 1141.94   856.3 1150.52   886.2 1163.98   896.1 1171.81     926 1202.12
   985.7 1249.28  1075.3 1305.93  1095.3 1312.04  1115.2 1320.39    1155 1344.85
#Mann= 3 , 0 , 0
       0      .1       0   469.1    .045       0   511.2      .1       0
Bank Sta=469.1,511.2
XS Rating Curve= 0 ,0
Exp/Cntr=0.3,0.1

Type RM Length L Ch R = 1 ,7556.6  ,339.9,346.1,352.2
XS GIS Cut Line= 2
      1746608.01      442295.306     1747248.954      442357.004
#Sta/Elev= 30
       0 1001.32    49.5 1001.34   148.6 1000.11   158.5  999.68   198.1  996.33
   267.5  994.88   277.4  994.33   287.3   993.2   307.1  986.54     317  985.43
   336.8   985.7   346.7  985.33   366.5  978.94   376.4  977.93   389.8  975.77
   396.2  974.77   406.2  974.69     426  974.69     435   975.2   445.8  978.17
   455.7  981.54   475.5  986.19   485.4  989.57   495.3  993.83   505.2 1000.25
   544.8 1033.89   574.6 1063.29   584.5 1071.44   614.2 1094.28   643.9 1114.76
#Mann= 3 , 0 , 0
       0     .08       0   389.8    .045       0     435      .1       0
Bank Sta=389.8,435
XS Rating Curve= 0 ,0
Exp/Cntr=0.3,0.1

Type RM Length L Ch R = 1 ,7210.5  ,475.4,461.8,448.3
XS GIS Cut Line= 2
     1746531.194      442514.944     1747114.951      442738.366
#Sta/Elev= 30
       0  997.22    39.7  996.31    49.6  997.01    59.5  999.69   109.1 1000.34
   119.1   999.6   138.9  994.66   158.7  993.97   208.4  995.84   228.2  999.76
   238.1 1000.27   307.6  994.54   317.5  992.99   347.2  982.27   357.2  980.35
   387.1  978.94   416.7  974.48   426.6  974.42   432.2  974.42   466.3  974.42
   476.2   982.7   486.2   997.1     506 1020.02   525.8 1034.91   545.7 1045.64
   555.6 1052.48   565.5 1057.12   575.4 1060.91   605.2 1067.56     625 1074.68
#Mann= 3 , 0 , 0
       0     .08       0   387.1    .045       0   432.2     .06       0
Bank Sta=387.1,432.2
XS Rating Curve= 0 ,0
Exp/Cntr=0.3,0.1

Type RM Length L Ch R = 1 ,6748.6  ,378.8,372.9,367.1
XS GIS Cut Line= 2
     1746737.639      443122.271     1747364.437      442974.825
#Sta/Elev= 30
       0  998.65     9.9  996.69    39.6   996.6    49.5  994.49    79.2  977.49
    89.2  974.59      92  974.47    99.1  974.16     109  974.16   118.9  983.15
   124.7   987.2   128.8  990.06   138.7  990.88   148.6   992.7   178.3 1004.12
   188.2 1006.09   198.1 1006.59   257.6 1013.78   267.5 1015.75   287.3 1022.14
   326.9 1030.25   376.4 1043.26   455.7    1067   505.2 1077.37   554.8 1090.55
   584.5 1099.46   604.3 1106.32   614.2 1105.34   624.1 1107.72   643.9 1114.95
#Mann= 3 , 0 , 0
       0     .08       0      92    .045       0   124.7     .06       0
Bank Sta=92,124.7
XS Rating Curve= 0 ,0
Exp/Cntr=0.3,0.1

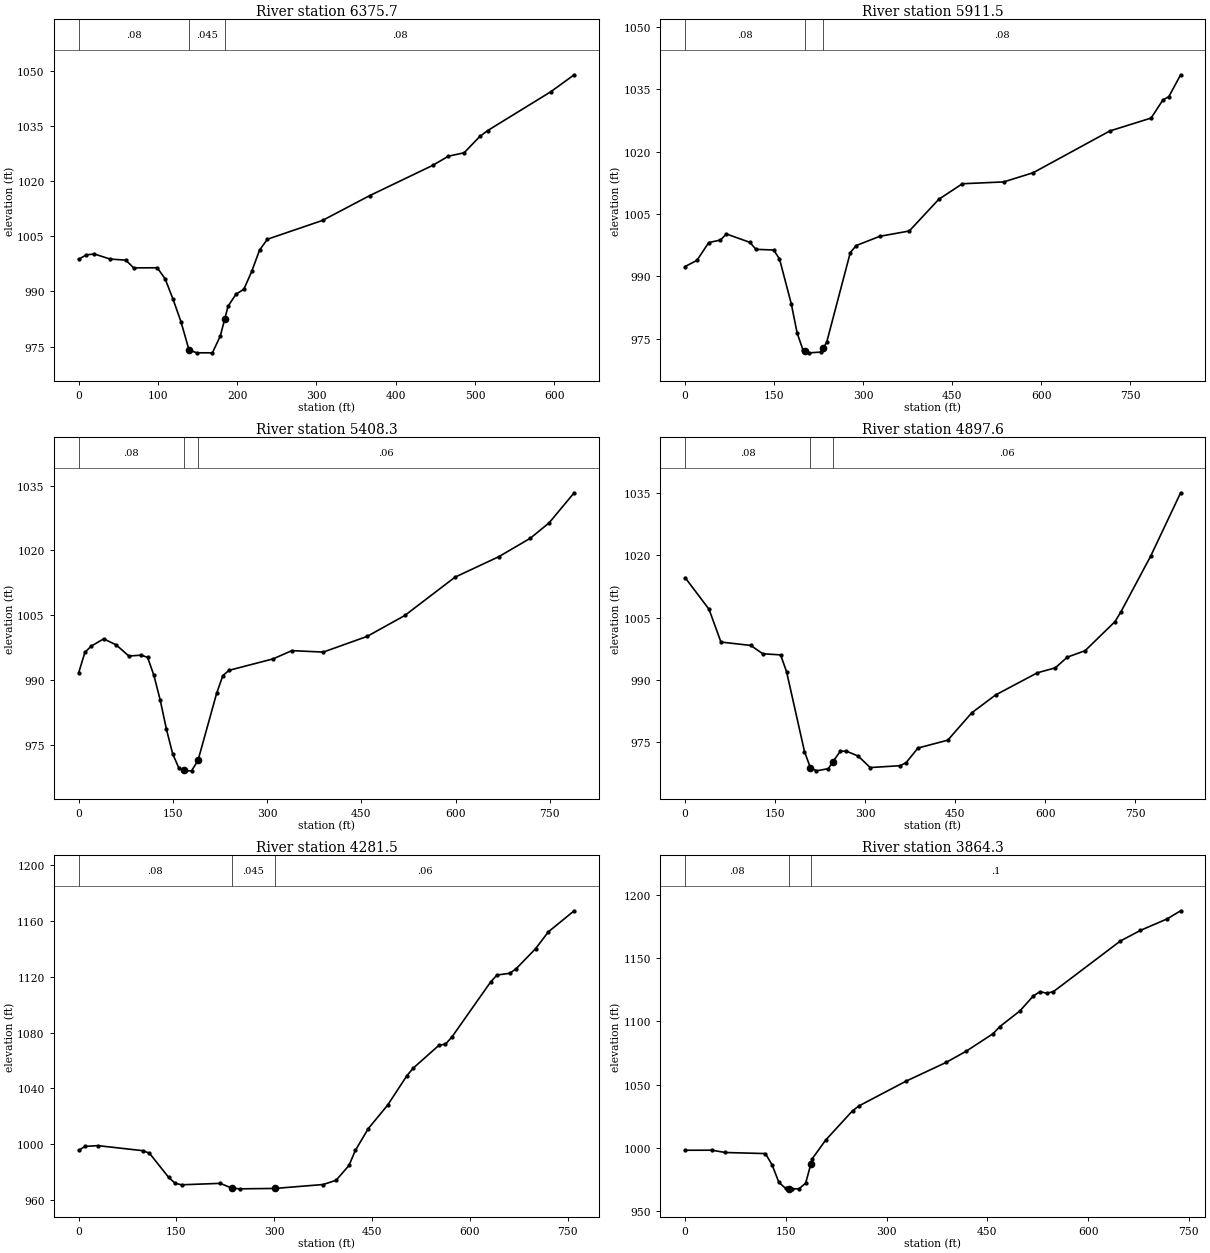
Type RM Length L Ch R = 1 ,6375.7  ,470.5,464.2,457.8
XS GIS Cut Line= 2
       1746825.1      443523.732     1747377.093      443230.487
#Sta/Elev= 30
       0  998.79     9.9  999.98    19.8 1000.21    39.7  998.83    59.5  998.54
    69.4  996.43    99.2  996.46   109.1  993.44   119.1  987.88     129  981.82
   139.2  974.11   148.8  973.31   168.7   973.3   178.6  977.83   184.2  982.45
   188.5     986   198.4  989.24   208.4  990.62   218.3  995.45   228.2 1001.28
   238.1 1004.23   307.6 1009.35   367.1  1016.1   446.5 1024.33   466.3 1026.83
   486.2 1027.77     506  1032.2   515.9 1033.81   595.3 1044.35     625    1049
#Mann= 3 , 0 , 0
       0     .08       0   139.2    .045       0   184.2     .08       0
Bank Sta=139.2,184.2
XS Rating Curve= 0 ,0
Exp/Cntr=0.3,0.1

Type RM Length L Ch R = 1 ,5911.5  ,513.7,503.2,492.7
XS GIS Cut Line= 2
     1747089.807      443963.833     1747689.907      443383.365
#Sta/Elev= 30
       0  992.34    19.9  993.81    39.8   998.1    59.6  998.72    69.6 1000.17
   109.3  998.15   119.3  996.47   149.1  996.32     159   994.2   178.9  983.35
   188.8  976.31   198.8  972.16     202  971.96   208.7  971.55   228.6  971.73
   232.6  972.68   238.5  974.07   278.3  995.67   288.2  997.38     328  999.61
   377.7 1000.89   427.4 1008.52   467.2 1012.27   536.7 1012.71   586.4 1014.92
   715.6 1024.98   785.2 1028.09   805.1 1032.47     815 1033.24   834.9 1038.51
#Mann= 3 , 0 , 0
       0     .08       0     202    .045       0   232.6     .08       0
Bank Sta=202,232.6
XS Rating Curve= 0 ,0
Exp/Cntr=0.3,0.1

Type RM Length L Ch R = 1 ,5408.3  ,512.2,510.7,509
XS GIS Cut Line= 2
     1747624.342      444217.736     1747883.864      443472.884
#Sta/Elev= 30
       0  991.64      10   996.4      20  997.84    39.9  999.52    59.9  998.12
    79.9  995.55    99.8  995.75   109.8  995.24   119.8  991.08   129.8  985.39
   139.8  978.58   149.8  972.87   159.8  969.54   167.3  969.12   169.7  968.98
   179.7  968.98     190  971.38   219.7  986.93   229.6  991.04   239.6  992.25
   309.5  994.89   339.5   996.8   389.4  996.46   459.3  1000.1   519.2 1004.93
   599.1  1013.8     669 1018.55   718.9  1022.8   748.8 1026.35   788.8 1033.33
#Mann= 3 , 0 , 0
       0     .08       0   167.3    .045       0     190     .06       0
Bank Sta=167.3,190
XS Rating Curve= 0 ,0
Exp/Cntr=0.3,0.1

Type RM Length L Ch R = 1 ,4897.6  ,603.6,616.1,628.4
XS GIS Cut Line= 2
     1748064.737      444470.604     1748279.646      443673.536
#Sta/Elev= 30
       0 1014.66    39.8 1007.03    59.7  999.11   109.4  998.29   129.3  996.29
   159.1  996.01   169.1  991.92   198.9  972.68   208.6  968.84   218.8  968.04
   238.7  968.57   245.7  970.13   258.6  972.78   268.6  972.79   288.4   971.6
   308.3  968.83   358.1  969.28     368  969.98   387.9  973.54   437.6  975.44
   477.4  982.02   517.2  986.34   586.8  991.69   616.7  992.88   636.6  995.46
   666.4  997.03   716.1 1004.03   726.1 1006.42   775.8  1019.9   825.5 1035.12
#Mann= 3 , 0 , 0
       0     .08       0   208.6    .045       0   245.7     .06       0
Bank Sta=208.6,245.7
XS Rating Curve= 0 ,0
Exp/Cntr=0.3,0.1

Type RM Length L Ch R = 1 ,4281.5  ,429.2,417.2,405.3
XS GIS Cut Line= 2
     1748545.137      444621.307     1748992.248       444006.72
#Sta/Elev= 30
       0  995.64     9.9  998.48    29.6  999.01    98.7  995.38   108.6  993.59
   138.2  976.18   148.1  971.99   157.9  970.94   217.2  971.97   234.6   968.6
   246.8  968.04   301.1  968.33   375.1  971.14   394.8  974.15   414.6  984.79
   424.4  995.58   444.2 1011.21   473.8 1027.99   503.4 1049.11   513.3 1054.63
   552.7 1070.99   562.6 1071.78   572.5  1076.9   631.7 1116.23   641.6 1121.34
   661.3 1122.57   671.2 1125.94   700.8 1140.21   720.5 1152.33     760 1167.39
#Mann= 3 , 0 , 0
       0     .08       0   234.6    .045       0   301.1     .06       0
Bank Sta=234.6,301.1
XS Rating Curve= 0 ,0
Exp/Cntr=0.3,0.1

Type RM Length L Ch R = 1 ,3864.3  ,423.8,421.4,418.9
XS GIS Cut Line= 2
     1748953.483       444794.86     1749152.063      444084.277
#Sta/Elev= 30
       0  998.26    39.9  998.29    59.8  996.48   119.6  995.63   129.6  986.61
   139.6  972.92   149.6  968.13     154  967.97   159.5  967.78   169.5  967.82
   179.5  972.22   187.4  987.72   189.4  991.65   209.4 1006.34   249.3 1029.42
   259.2 1033.37     329 1052.83   388.8 1067.65   418.8 1076.57   458.6 1090.33
   468.6 1095.92   498.5  1108.3   518.5 1120.14   528.4 1123.52   538.4 1122.28
   548.4 1123.52   648.1 1163.52     678 1171.89   717.9 1181.02   737.8 1187.38
#Mann= 3 , 0 , 0
       0     .08       0     154    .045       0   187.4      .1       0
Bank Sta=154,187.4
XS Rating Curve= 0 ,0
Exp/Cntr=0.3,0.1

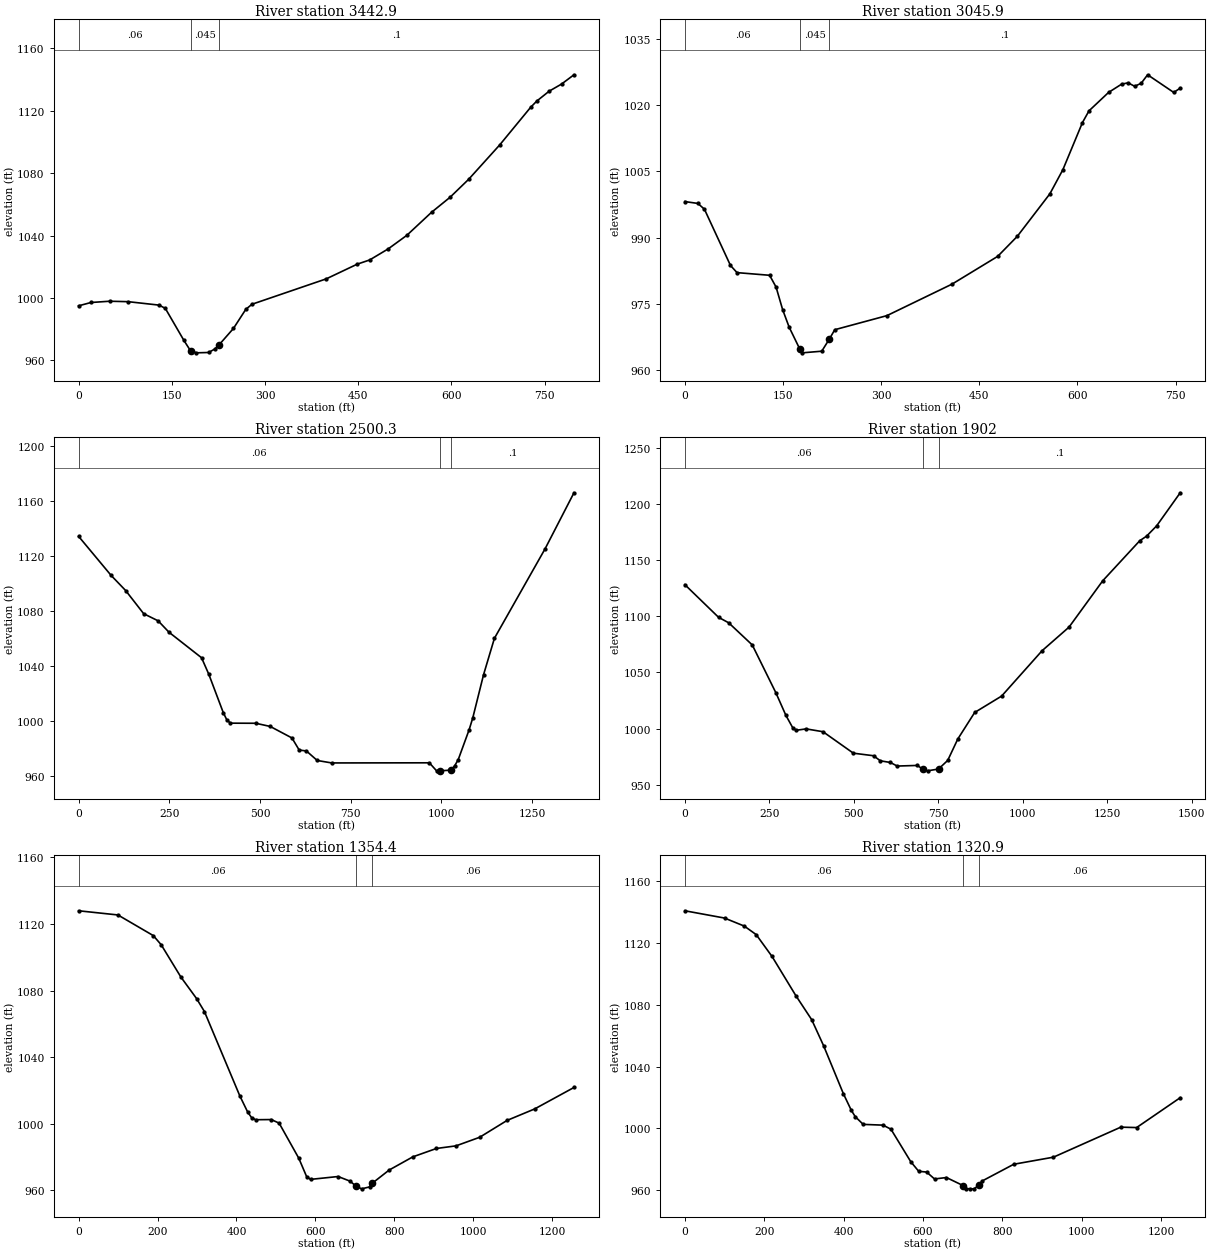
Type RM Length L Ch R = 1 ,3442.9  ,400.1,397,393.8
XS GIS Cut Line= 2
     1749362.864      444964.786     1749487.096      444177.458
#Sta/Elev= 30
       0  994.96    19.9  997.08    49.8  997.89    79.7  997.61   129.5   995.4
   139.5  993.32   169.4   972.8   179.3  966.62   181.1   966.3   189.3  964.82
   209.2  965.05   219.2   967.3   226.1  969.99   249.1  980.43     269  992.68
     279  995.96   398.5 1012.23   448.4 1021.66   468.3 1024.33   498.2 1031.44
   528.1 1040.11   567.9 1054.88   597.8 1064.54   627.7 1076.05   677.5 1098.01
   727.3 1122.12   737.3 1126.18   757.2  1132.5   777.1 1137.06   797.1 1143.01
#Mann= 3 , 0 , 0
       0     .06       0   181.1    .045       0   226.1      .1       0
Bank Sta=181.1,226.1
XS Rating Curve= 0 ,0
Exp/Cntr=0.3,0.1

Type RM Length L Ch R = 1 ,3045.9  ,530.7,545.6,559.4
XS GIS Cut Line= 2
     1749785.639      444999.365     1749796.682      444242.406
#Sta/Elev= 30
       0  998.16    19.9  997.74    29.9  996.43    69.7  983.72    79.7   982.1
   129.5   981.5   139.4  978.83   149.4  973.74   159.4  969.76   175.9  964.74
   179.3  963.97   209.2  964.34   220.9  967.11   229.1   969.2   308.8  972.38
   408.4  979.51   478.1  985.78     508   990.3   557.8  999.91   577.7 1005.37
   607.6 1016.02   617.6 1018.67   647.5 1022.83   667.4  1024.7   677.4    1025
   687.3 1024.22   697.3 1024.89   707.2 1026.82   747.1 1022.83     757  1023.8
#Mann= 3 , 0 , 0
       0     .06       0   175.9    .045       0   220.9      .1       0
Bank Sta=175.9,220.9
XS Rating Curve= 0 ,0
Exp/Cntr=0.3,0.1

Type RM Length L Ch R = 1 ,2500.3  ,586.2,598.3,609.2
XS GIS Cut Line= 2
     1749612.512      445444.285     1750437.021      444355.546
#Sta/Elev= 30
       0 1134.24    89.7 1105.82   129.6 1094.88   179.4 1078.01   219.3 1072.81
   249.2 1064.53   338.9 1045.99   358.9 1033.99   398.8  1006.1   408.7 1000.75
   418.7  998.41   488.5  998.33   528.3  996.02   588.2  987.64   608.1  978.87
     628  978.19   657.9  971.27   697.8  969.48     967  969.58   986.9  963.75
   996.3  963.74  1025.8  964.25  1036.7  967.33  1046.7  971.95  1076.6  993.57
  1086.6 1002.12  1116.5 1033.71  1146.4 1060.14    1286 1125.17  1365.7 1165.95
#Mann= 3 , 0 , 0
       0     .06       0   996.3    .045       0  1025.8      .1       0
Bank Sta=996.3,1025.8
XS Rating Curve= 0 ,0
Exp/Cntr=0.3,0.1

Type RM Length L Ch R = 1 ,1902    ,551.3,547.6,543.9
XS GIS Cut Line= 2
     1749798.993       445488.53     1751131.212      444876.178
#Sta/Elev= 30
       0 1128.18    99.7 1099.11   129.7 1094.22   199.5  1074.5   269.3 1031.98
   299.2 1011.72   319.2 1000.82   329.2  998.53   359.1  999.77   408.9  997.25
   498.7  978.15   558.6  975.87   578.5  971.36   608.4  969.87   628.4  966.69
   688.2  967.24   705.2  963.68   718.2  962.43   750.8  964.04     778  971.71
   807.9  990.78   857.8 1014.38   937.6 1028.99  1057.3 1069.35  1137.1 1090.37
  1236.8  1131.6  1346.5  1167.3  1366.5 1171.31  1396.4 1180.51  1466.2 1209.97
#Mann= 3 , 0 , 0
       0     .06       0   705.2    .045       0   750.8      .1       0
Bank Sta=705.2,750.8
XS Rating Curve= 0 ,0
Exp/Cntr=0.3,0.1

Type RM Length L Ch R = 1 ,1354.4  ,33.5,33.5,33.5
XS GIS Cut Line= 2
     1750117.671      446070.319     1751157.509      445366.863
#Sta/Elev= 30
       0 1127.96    99.6 1125.45   189.3 1113.04   209.2 1107.57   259.1 1088.18
   298.9 1075.24   318.8 1067.44   408.5 1016.78   428.4 1007.07   438.4 1003.68
   448.4 1002.44   488.2 1002.54   508.2 1000.38     558  979.31   577.9  968.23
   587.9   966.6   657.6  968.32   687.5  965.58   703.9  962.41   717.4  960.92
   737.3  962.08   743.5  964.16   787.1  972.22   846.9  980.12   906.7  985.16
   956.5  986.74  1016.3  991.88    1086 1002.04  1155.8 1008.92  1255.4 1021.81
#Mann= 3 , 0 , 0
       0     .06       0   703.9    .045       0   743.5     .06       0
Bank Sta=703.9,743.5
XS Rating Curve= 0 ,0
Exp/Cntr=0.3,0.1

Type RM Length L Ch R = 1 ,1320.9  ,424.3,403,381.7
XS GIS Cut Line= 2
     1750138.717      446096.491     1751172.606      445397.059
#Sta/Elev= 30
       0 1140.72    99.9 1136.02   149.8 1130.81   179.8 1125.29   219.7 1111.16
   279.6 1085.86   319.6 1070.29   349.5 1053.51   399.4 1022.45   419.4 1011.69
   429.4 1007.56   449.4 1002.59   499.3  1002.1   519.3  999.47   569.2  978.47
   589.2  972.26   609.2  971.75   629.1   967.3   659.1  968.22   701.9  962.92
     709  961.08     719  960.91     729  960.91   741.1  963.43     749  965.97
   828.8  976.81   928.7  981.38  1098.5  1000.8  1138.4 1000.53  1248.2 1019.84
#Mann= 3 , 0 , 0
       0     .06       0   701.9    .045       0   741.1     .06       0
Bank Sta=701.9,741.1
XS Rating Curve= 0 ,0
Exp/Cntr=0.3,0.1

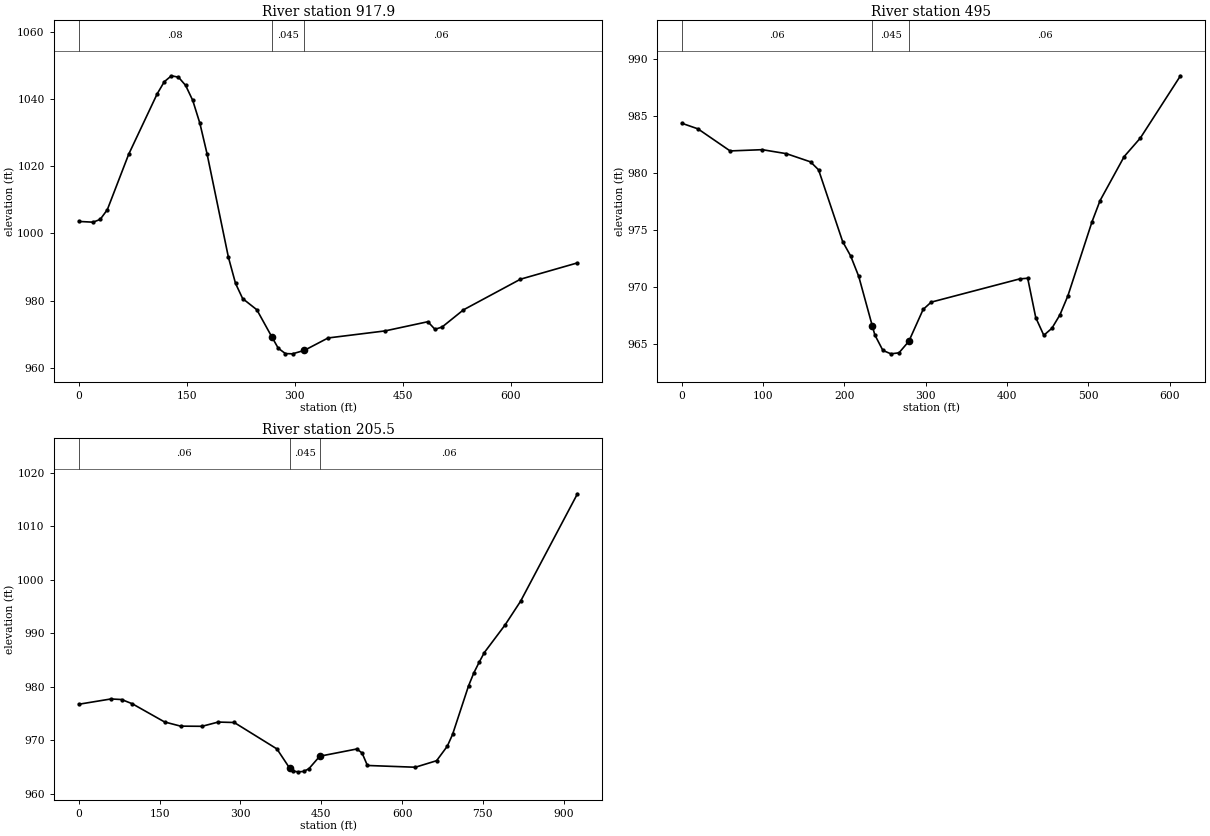
Type RM Length L Ch R = 1 ,917.9   ,429.2,423,416.8
XS GIS Cut Line= 2
     1751016.413      446240.924     1751040.545      445549.084
#Sta/Elev= 30
       0 1003.56    19.8 1003.34    29.7 1004.16    39.6 1007.05    69.2 1023.54
   108.8 1041.56   118.7 1045.19   128.6 1046.96   138.4 1046.54   148.3  1044.1
   158.2 1039.62   168.1 1032.81     178 1023.78   207.7  992.91   217.6   985.1
   227.5  980.57   247.2  977.24   267.9   969.2   276.9  965.79   286.8  964.19
   296.7  964.11   313.3  965.16   346.1  968.84   425.2  970.94   484.6  973.68
   494.5  971.42   504.4   972.1     534  977.21   613.2  986.35   692.3  991.21
#Mann= 3 , 0 , 0
       0     .08       0   267.9    .045       0   313.3     .06       0
Bank Sta=267.9,313.3
XS Rating Curve= 0 ,0
Exp/Cntr=0.3,0.1

Type RM Length L Ch R = 1 ,495     ,293.1,289.4,285.8
XS GIS Cut Line= 2
      1751504.34      446160.787     1751357.968      445565.173
#Sta/Elev= 30
       0  984.35    19.8  983.86    59.4  981.92    98.9  982.03   128.6  981.68
   158.3  980.96   168.2  980.26   197.8  973.96   207.7  972.69   217.6   970.9
   234.2  966.57   237.4  965.76   247.3   964.4   257.2   964.1   267.1  964.19
   279.2   965.2   296.8     968   306.7  968.64   415.5  970.68   425.4  970.74
   435.3  967.28   445.2  965.73   455.1  966.34     465  967.52   474.8  969.19
   504.5   975.7   514.4  977.56   544.1  981.43   563.9  983.05   613.3  988.52
#Mann= 3 , 0 , 0
       0     .06       0   234.2    .045       0   279.2     .06       0
Bank Sta=234.2,279.2
XS Rating Curve= 0 ,0
Exp/Cntr=0.3,0.1

Type RM Length L Ch R = 1 ,205.5   ,212.4,205.5,198.6
XS GIS Cut Line= 4
     1751646.256      446228.472     1751763.022      445932.315
     1751596.292      445541.736      1751465.07      445415.145
#Sta/Elev= 30
       0  976.73    59.7  977.72    79.6  977.61    99.5  976.81   159.2  973.42
     189  972.64   228.8  972.61   258.6   973.4   288.5  973.32   367.7  968.38
   391.1  964.82   397.4  964.23   407.2   964.1   417.1  964.17     427  964.68
   447.2  967.02   515.9  968.37   525.7  967.62   535.6  965.29   624.5  964.96
     664  966.18   683.8  968.88   693.6  971.08   723.3  980.17   733.2  982.61
     743  984.58   752.6  986.39     791  991.54   819.8  995.97   925.4 1016.06
#Mann= 3 , 0 , 0
       0     .06       0   391.1    .045       0   447.2     .06       0
Bank Sta=391.1,447.2
XS Rating Curve= 0 ,0
Exp/Cntr=0.3,0.1

Chan Stop Cuts=-1
Use User Specified Reach Order=0
Composite Channel Slope=5